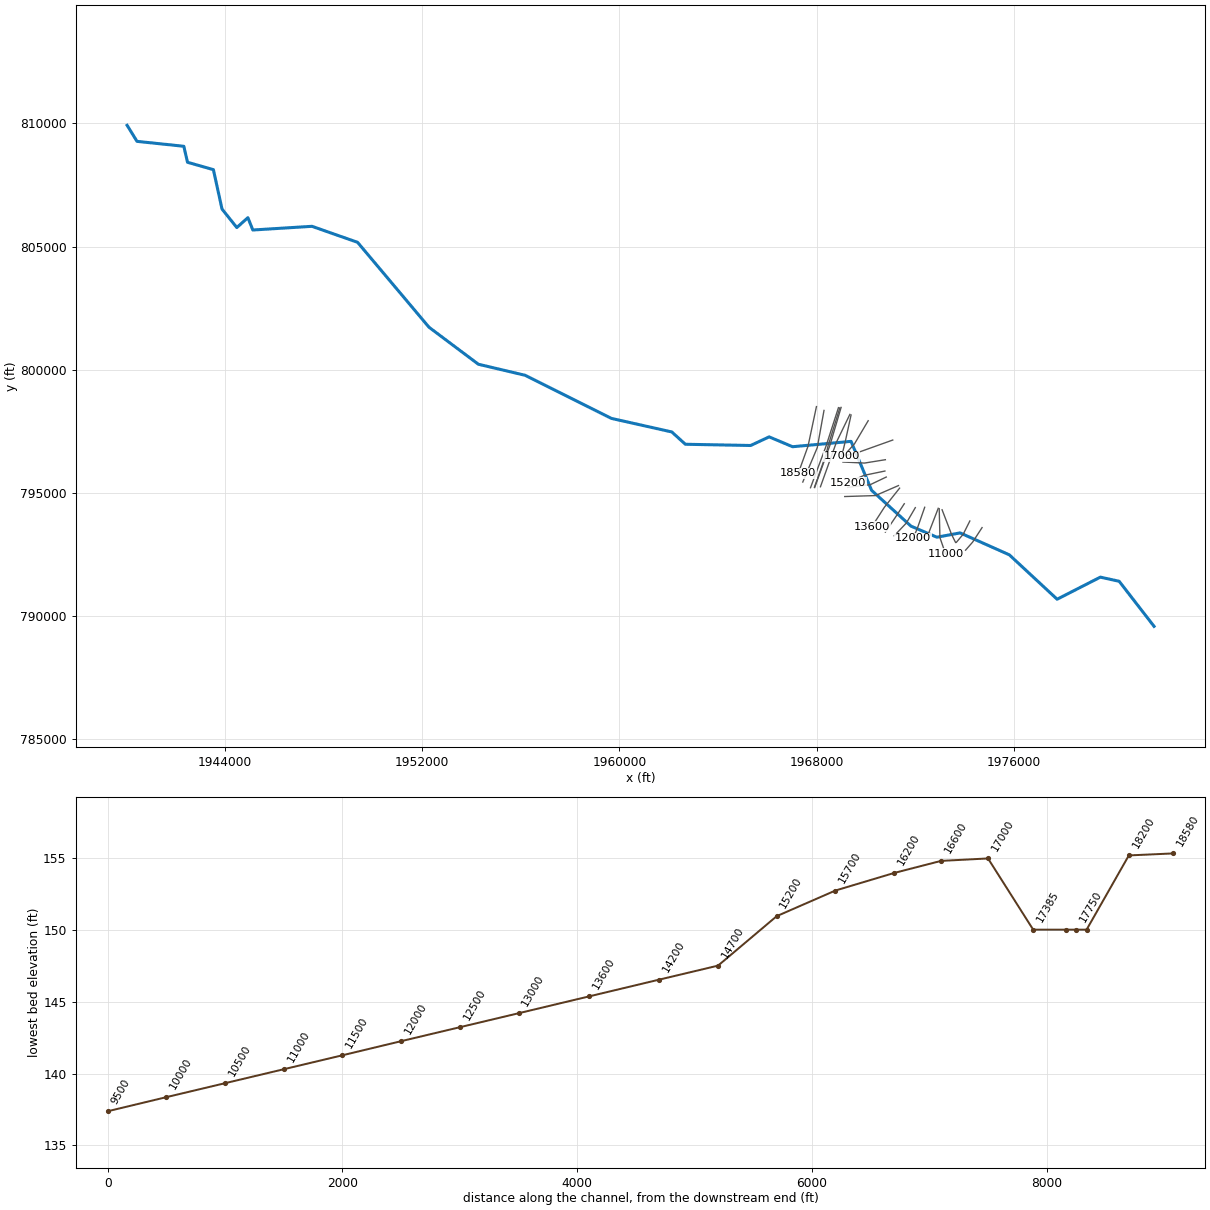
--- SALUDA RIVER.prj (project) ---

Proj Title=SALUDA RIVER Detailed Study
Current Plan=p01
Default Exp/Contr=0.3,0.1
English Units
Geom File=g01
Flow File=f01
Flow File=f02
Plan File=p01
Plan File=p02
Y Axis Title=Elevation
X Axis Title(PF)=Main Channel Distance
X Axis Title(XS)=Station
BEGIN DESCRIPTION:
SALUDA RIVER
END DESCRIPTION:
DSS Export Rating Curves= 0
DSS Export Rating Curve Sorted= 0
DSS Export Volume Flow Curves= 0
DXF OffsetX= 0
DXF OffsetY= 0
DXF ScaleX= 1
DXF ScaleY= 10

--- SALUDA RIVER.p01 (plan) ---

Plan Title=Multiple Run
Short Identifier=Multiple
Geom File=g01
Flow File=f01
Subcritical Flow
K Sum by GR= 0
Std Step Tol= 0.01
Critical Tol= 0.01
Num of Std Step Trials= 20
Max Error Tol= 0.3
Flow Tol Ratio= 0.001
Split Flow NTrial= 30
Split Flow Tol= 0.02
Split Flow Ratio= 0.02
Log Output Level= 0
Friction Slope Method= 1
Unsteady Friction Slope Method= 2
Unsteady Bridges Friction Slope Method= 1
Parabolic Critical Depth
Global Vel Dist=  1 , 1 , 1
Global Log Level= 0
CheckData=True
Encroach Param= -1, 0, 0, 0
BEGIN DESCRIPTION:
Multiple Run
END DESCRIPTION:

--- SALUDA RIVER.p02 (plan) ---

Plan Title=Floodway Run
Short Identifier=Floodway
Geom File=g01
Flow File=f02
Subcritical Flow
K Sum by GR= 0
Std Step Tol= 0.01
Critical Tol= 0.01
Num of Std Step Trials= 20
Max Error Tol= 0.3
Flow Tol Ratio= 0.001
Split Flow NTrial= 30
Split Flow Tol= 0.02
Split Flow Ratio= 0.02
Log Output Level= 0
Friction Slope Method= 1
Unsteady Friction Slope Method= 2
Unsteady Bridges Friction Slope Method= 1
Parabolic Critical Depth
Global Vel Dist=  1 , 1 , 1
Global Log Level= 0
CheckData=True
Encroach Param=-1,0,0,2
Encroach River=SALUDA RIVER
Encroach Reach=Reach-1
Encroach Node=18580
       1    3965    5393
Encroach Node=18200
       1    4500    5425
Encroach Node=17840
       1    4800    5200
Encroach Node=17790
       1    4800    5200
Encroach Node=17750
       1    4800    5200
Encroach Node=17665
       1    4660    5290
Encroach Node=17540
       1    4660    5290
Encroach Node=17385
       1    4635    5285
Encroach Node=17000
       1    4700    5300
Encroach Node=16600
       1    4700    5300
Encroach Node=16200
       1    4640    5350
Encroach Node=15700
       1    4700    5500
Encroach Node=15200
       1    4640    5560
Encroach Node=14700
       1    4735    5598
Encroach Node=14200
       1    4800    5540
Encroach Node=13600
       1    4800    5500
Encroach Node=13000
       1    4821    5340
Encroach Node=12500
       1    4821    5382
Encroach Node=12000
       1    4842    5120
Encroach Node=11500
       1    4839    5215
Encroach Node=11000
       1    4834    5179
Encroach Node=10500
       1    4801    5195
Encroach Node=10000
       1    4820    5205
Encroach Node=9500
       1    4810    5220
Encroach Node=9000
       1    4817    5200
Encroach Node=8500
       1    4728    5285
Encroach Node=8240
       1    4640    5465
Encroach Node=7900
       1    4720    5565
Encroach Node=7400
       1    4728    5253
Encroach Node=6900
       1    4762    5167
Encroach Node=6450
       1    4730    5193
Encroach Node=6350
       1    4730    5193
Encroach Node=6270
       1    4719    5204
Encroach Node=5900
       1    4830    5165
Encroach Node=5400
       1    4795    5150
Encroach Node=4900
       1    4830    5150
Encroach Node=4400
       1    4880    5150
Encroach Node=3900
       1    4860    5150
Encroach Node=3400
       1    4844    5150
Encroach Node=2900
       1    4700    5275
Encroach Node=2400
       1    4550    5675
Encroach Node=2000
       1    4750    5700
Encroach Node=1600
       1    4750    5600
Encroach Node=1100
       1    4750    5350
BEGIN DESCRIPTION:
Floodway Run
END DESCRIPTION:

--- SALUDA RIVER.f01 (steady flow) ---

Flow Title=Multiple
Number of Profiles=5
Profile Names=10-year,25-year,50-year,100-year,500-year
River Rch & RM= SALUDA RIVER,Reach-1,18580
   29600   39400   48300   58600   89900
River Rch & RM= SALUDA RIVER,Reach-1,17665
   29600   39400   48300   58600   89900
Boundary for River Rch & Prof#=SALUDA RIVER,Reach-1,1
Up Type=0
Dn Type=3
Dn Slope=0.00105
Boundary for River Rch & Prof#=SALUDA RIVER,Reach-1,2
Up Type=0
Dn Type=3
Dn Slope=0.00105
Boundary for River Rch & Prof#=SALUDA RIVER,Reach-1,3
Up Type=0
Dn Type=3
Dn Slope=0.00105
Boundary for River Rch & Prof#=SALUDA RIVER,Reach-1,4
Up Type=0
Dn Type=3
Dn Slope=0.00105
Boundary for River Rch & Prof#=SALUDA RIVER,Reach-1,5
Up Type=0
Dn Type=3
Dn Slope=0.00105

--- SALUDA RIVER.f02 (steady flow) ---

Flow Title=Floodway
Number of Profiles=2
Profile Names=100-year,100-FW
River Rch & RM= SALUDA RIVER,Reach-1,18580
   58600   58600
River Rch & RM= SALUDA RIVER,Reach-1,17665
   58600   58600
Boundary for River Rch & Prof#=SALUDA RIVER,Reach-1,1
Up Type=0
Dn Type=3
Dn Slope=0.00105
Boundary for River Rch & Prof#=SALUDA RIVER,Reach-1,2
Up Type=0
Dn Type=3
Dn Slope=0.00105

--- SALUDA RIVER.g01 (geometry) ---

Geom Title=Existing Conditions

River Reach=SALUDA RIVER,Reach-1
Reach XY= 30
      1940025.00       809925.00      1940425.00       809275.00
      1942325.00       809075.00      1942475.00       808425.00
      1943525.00       808125.00      1943875.00       806525.00
      1944475.00       805775.00      1944925.00       806175.00
      1945125.00       805675.00      1947525.00       805825.00
      1949375.00       805175.00      1952275.00       801725.00
      1954275.00       800225.00      1956175.00       799775.00
      1959675.00       798025.00      1962125.00       797475.00
      1962675.00       796975.00      1965325.00       796925.00
      1966075.00       797275.00      1967025.00       796875.00
      1969399.00       797092.60      1970231.69       795104.72
      1971830.25       793650.36      1972881.79       793200.27
      1973823.05       793375.80      1975820.27       792485.86
      1977760.18       790682.11      1979514.91       791579.55
      1980277.87       791410.79      1981693.76       789580.30

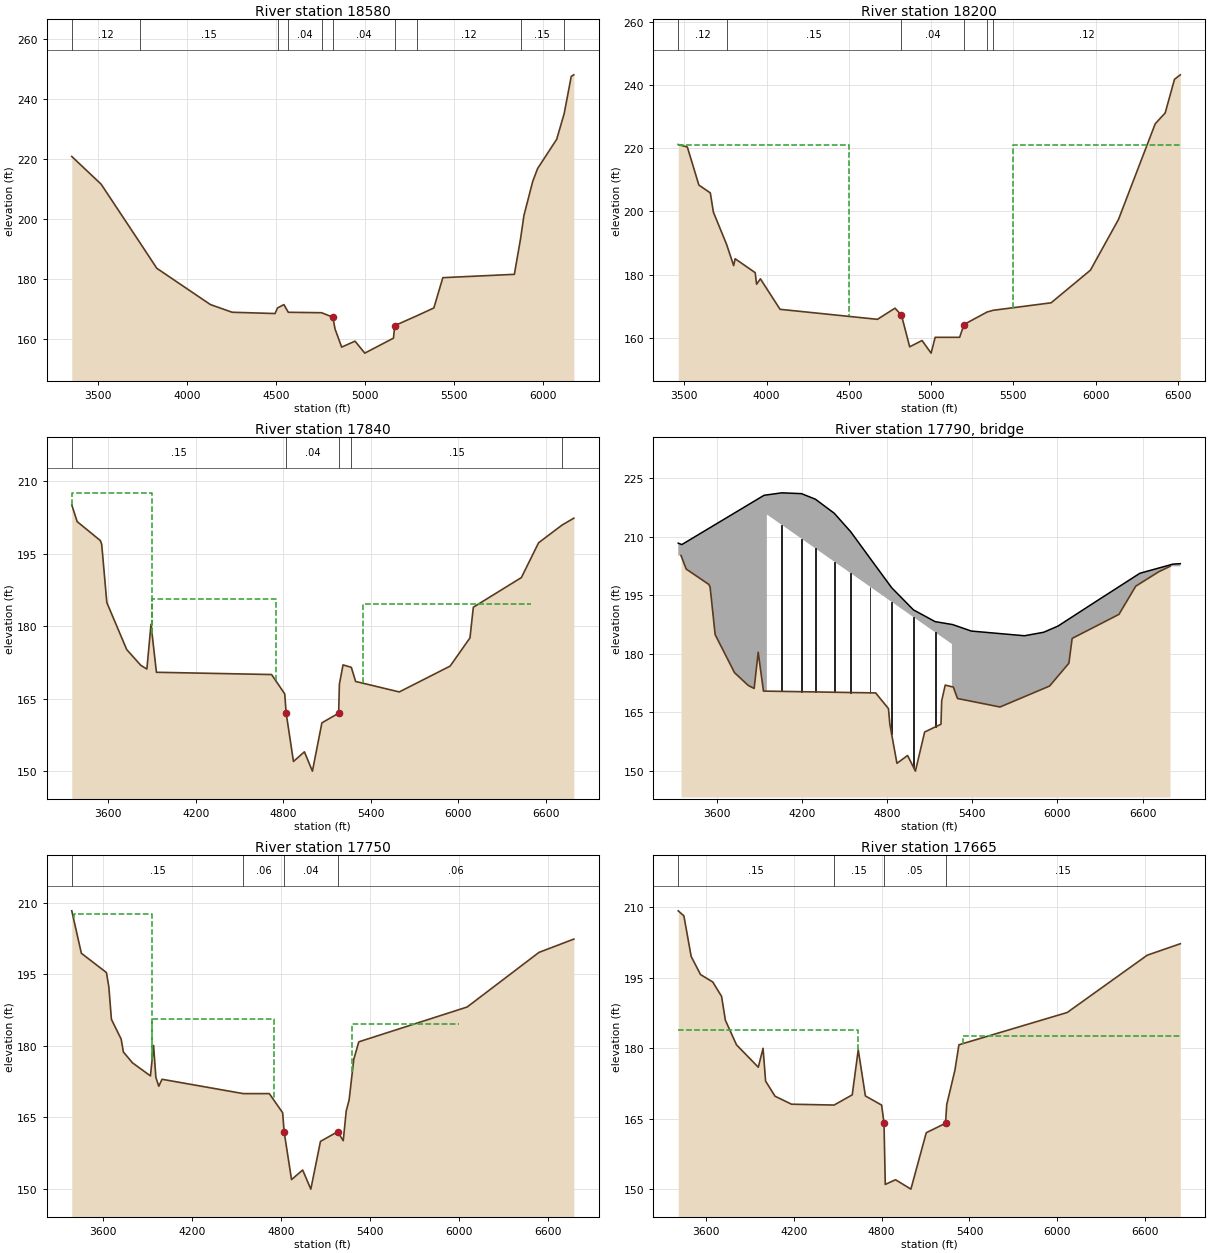
Type RM Length L Ch R = 1,18580,369,380,360
BEGIN DESCRIPTION:
SALUDA RIVER 45.0
END DESCRIPTION:
XS GIS Cut Line= 3
      1967994.19       798504.51      1967652.00       796893.35
      1967253.26       795788.08
#Sta/Elev= 30
  3352.9  220.87  3517.8  211.64  3733.9  192.32  3830.8  183.59  4132.3  171.49
  4254.4  168.93  4495.5  168.50  4509.4  170.37  4545.2  171.47  4570.0  168.92
  4757.1  168.77  4820.0  167.30  4833.0  163.30  4870.0  157.30  4945.0  159.30
  5000.0  155.30  5161.3  160.30  5168.1  164.46  5295.1  167.82  5388.1  170.36
  5438.6  180.46  5840.6  181.57  5875.2  193.34  5894.7  201.26  5943.8  212.54
  5971.3  216.85  6078.6  226.60  6120.9  235.23  6160.4  247.58  6175.0  248.09
#Mann=10,-1,0
  3352.9    0.12       0  3733.9    0.15       0  4509.4    0.08       0
  4570.0    0.04       0  4757.1    0.15       0  4820.0    0.04       0
  5168.1    0.15       0  5295.1    0.12       0  5875.2    0.15       0
  6120.9    0.12       0
Bank Sta=4820,5168.1
Exp/Cntr=0.3,0.1

Type RM Length L Ch R = 1,18200,399,360,425
BEGIN DESCRIPTION:
SALUDA RIVER 44.0
END DESCRIPTION:
XS GIS Cut Line= 3
      1968300.98       798348.76      1968027.38       796836.81
      1967440.11       795441.03
#Sta/Elev= 30
  3463.5  221.20  3518.9  220.41  3589.0  208.36  3658.5  205.88  3677.1  199.80
  3757.0  189.63  3800.2  182.87  3809.3  185.04  3931.2  180.63  3939.6  176.98
  3962.8  178.68  4082.2  169.03  4674.2  165.86  4780.6  169.39  4820.0  167.16
  4870.0  157.16  4945.0  159.16  5000.0  155.16  5024.7  160.16  5173.5  160.17
  5199.8  164.22  5340.1  168.17  5377.5  168.72  5729.2  171.09  5968.2  181.42
  6138.8  197.50  6361.9  227.77  6422.4  231.20  6479.0  241.85  6514.3  243.26
#Mann=6,-1,0
  3463.5    0.12       0  3757.0    0.15       0  4820.0    0.04       0
  5199.8    0.15       0  5340.1    0.04       0  5377.5    0.12       0
#XS Ineff=2,0
    0.00 4500.00  221.00 5500.00    0.00  221.00
Permanent Ineff=
       F       F
Bank Sta=4820,5199.8
Exp/Cntr=0.5,0.3

Type RM Length L Ch R = 1,17840,77,90,170
BEGIN DESCRIPTION:
SALUDA RIVER (I-26 Ramp - US)
END DESCRIPTION:
XS GIS Cut Line= 3
      1968887.40       798461.11      1968380.66       796890.12
      1967753.47       795210.18
#Sta/Elev= 30
  3349.3  205.13  3386.2  201.67  3545.5  197.74  3554.5  197.01  3589.8  184.91
  3726.1  175.18  3822.5  171.92  3864.5  171.14  3892.9  180.40  3930.0  170.47
  4720.0  170.00  4810.0  166.00  4820.0  162.00  4870.0  152.00  4945.0  154.00
  5000.0  150.00  5065.0  160.00  5180.0  162.00  5185.0  168.00  5210.0  172.00
  5267.1  171.49  5296.2  168.57  5595.7  166.40  5944.6  171.75  6080.7  177.59
  6103.7  183.94  6433.2  190.08  6551.5  197.29  6712.6  200.96  6793.2  202.38
#Mann=5,-1,0
  3349.3    0.15       0  4820.0    0.04       0  5180.0    0.04       0
  5267.1    0.15       0  6712.6    0.11       0
#XS Ineff=3,-1
 3300.00 3900.00  207.63 3900.10 4750.00  185.70 5350.00 6500.00  184.62
Permanent Ineff=
       F       F       F
Bank Sta=4820,5180
Exp/Cntr=0.5,0.3

Type RM Length L Ch R =3,17790,,,
BEGIN DESCRIPTION:
SALUDA RIVER (I-26 Ramp - TOR)
Structure ID: I-26 Ramp
Detailed Survey Structure
END DESCRIPTION:
Bridge Culvert--1,0,-1,-1,0
Deck Dist Width WeirC Skew NumUp NumDn MinLoCord MaxHiCord MaxSubmerge Is_Ogee
32.5,35,3,,25,25,,,0.95,0,1,1,,
  3329.9  3354.9  3934.1  3954.1  3954.1  4059.4  4197.7  4295.9  4428.4  4545.0
  4680.0  4833.0  4986.0  5139.0  5257.0  5257.0  5262.0  5393.9  5767.8  5903.8
  6004.1  6281.0  6580.6  6813.7  6865.3
  208.30  207.93  220.54  220.64  220.64  221.17  220.96  219.54  215.95  211.19
  204.47  196.90  191.24  188.23  187.51  187.51  187.48  185.82  184.62  185.52
  187.10  193.61  200.60  202.94  203.05
  130.00  130.00  130.00  130.00  215.64  212.96  209.45  206.95  203.58  200.61
  197.18  193.29  189.40  185.51  182.51  130.00  130.00  130.00  130.00  130.00
  130.00  130.00  130.00  130.00  130.00
  3329.9  3354.9  3934.1  3954.1  3954.1  4059.4  4197.7  4295.9  4428.4  4545.0
  4680.0  4833.0  4986.0  5139.0  5257.0  5257.0  5262.0  5393.9  5767.8  5903.8
  6004.1  6281.0  6580.6  6813.7  6865.3
  208.30  207.93  220.54  220.64  220.64  221.17  220.96  219.54  215.95  211.19
  204.47  196.90  191.24  188.23  187.51  187.51  187.48  185.82  184.62  185.52
  187.10  193.61  200.60  202.94  203.05
  130.00  130.00  130.00  130.00  215.64  212.96  209.45  206.95  203.58  200.61
  197.18  193.29  189.40  185.51  182.51  130.00  130.00  130.00  130.00  130.00
  130.00  130.00  130.00  130.00  130.00
Pier Skew, UpSta & Num, DnSta & Num=,4059.4,2,4059.4,2,0,0,0,0,0
       5       5
  194.50  212.96
       5       5
  194.50  212.96
Pier Skew, UpSta & Num, DnSta & Num=,4197.7,2,4197.7,2,0,0,0,0,0
       5       5
  192.72  209.45
       5       5
  192.72  209.45
Pier Skew, UpSta & Num, DnSta & Num=,4295.9,2,4295.9,2,0,0,0,0,0
       5       5
  177.00  206.95
       5       5
  177.00  206.95
Pier Skew, UpSta & Num, DnSta & Num=,4428.4,2,4428.4,2,0,0,0,0,0
       5       5
  168.00  203.58
       5       5
  168.00  203.58
Pier Skew, UpSta & Num, DnSta & Num=,4545,2,4545,2,0,0,0,0,0
       5       5
  168.00  200.62
       5       5
  168.00  200.62
Pier Skew, UpSta & Num, DnSta & Num=,4680,2,4680,2,0,0,0,0,0
       5       5
  168.00  197.18
       5       5
  168.00  197.18
Pier Skew, UpSta & Num, DnSta & Num=,4833,2,4833,2,0,0,0,0,0
       5       5
  156.00  193.29
       5       5
  156.00  193.29
Pier Skew, UpSta & Num, DnSta & Num=,4986,2,4986,2,0,0,0,0,0
       5       5
  150.00  189.40
       5       5
  150.00  189.40
Pier Skew, UpSta & Num, DnSta & Num=,5139,2,5139,2,0,0,0,0,0
       5       5
  160.00  185.51
       5       5
  160.00  185.51
BR Coef=1,1,0,1.25,0,,,0.8,0,2,0,
WSPro=,,,, 1 ,,,, 0 ,,,, 0 ,,,,-1 ,-1 ,-1 , 0 , 0 , 0 , 0 , 0
BC Design=,,0,,0,,,,,,

Type RM Length L Ch R = 1,17750,67,85,34
BEGIN DESCRIPTION:
SALUDA RIVER (I-26 Ramp - DS)
END DESCRIPTION:
XS GIS Cut Line= 4
      1968944.07       798454.82      1968467.06       796915.33
      1968381.51       796550.92      1967913.41       795232.68
#Sta/Elev= 30
  3388.3  208.27  3453.1  199.38  3622.1  195.35  3638.3  192.33  3655.6  185.56
  3721.3  181.41  3736.2  178.72  3797.8  176.44  3918.8  173.71  3939.8  180.09
  3955.3  173.41  3974.8  171.54  3996.8  173.00  4544.2  170.00  4720.0  170.00
  4810.0  166.00  4820.0  162.00  4870.0  152.00  4945.0  154.00  5000.0  150.00
  5065.0  160.00  5180.0  162.00  5218.6  160.15  5238.6  166.36  5258.2  168.68
  5289.6  177.18  5323.3  180.84  6053.8  188.13  6538.3  199.57  6773.2  202.35
#Mann=4,-1,0
  3388.3    0.15       0  4544.2    0.06       0  4820.0    0.04       0
  5180.0    0.06       0
#XS Ineff=3,-1
 3400.00 3930.00  207.63 3930.10 4750.00  185.70 5279.50 6000.00  184.62
Permanent Ineff=
       F       F       F
Bank Sta=4820,5180
Exp/Cntr=0.5,0.3

Type RM Length L Ch R = 1,17665,289,280,372
BEGIN DESCRIPTION:
SALUDA RIVER (I-26 - US)
END DESCRIPTION:
XS GIS Cut Line= 3
      1968995.05       798471.57      1968545.83       796947.19
      1967921.81       795215.91
#Sta/Elev= 30
  3410.8  209.19  3449.3  208.12  3499.3  199.48  3563.3  195.63  3646.7  194.05
  3706.9  190.99  3732.8  185.92  3809.0  180.68  3957.6  175.93  3990.3  179.95
  4007.6  172.97  4071.7  169.77  4184.8  168.06  4475.5  167.88  4599.3  170.05
  4640.4  179.64  4689.3  169.82  4800.2  167.87  4816.4  164.00  4825.0  151.00
  4895.0  152.00  5000.0  150.00  5105.0  162.00  5236.4  164.00  5245.0  168.00
  5300.6  175.27  5328.0  180.70  6068.0  187.57  6614.2  199.75  6840.3  202.19
#Mann=4,-1,0
  3410.8    0.15       0  4475.5    0.15       0  4816.4    0.05       0
  5236.4    0.15       0
#XS Ineff=2,0
    0.00 4641.50  183.88 5356.50    0.00  182.67
Permanent Ineff=
       F       F
Bank Sta=4816.4,5236.4
Exp/Cntr=0.5,0.3

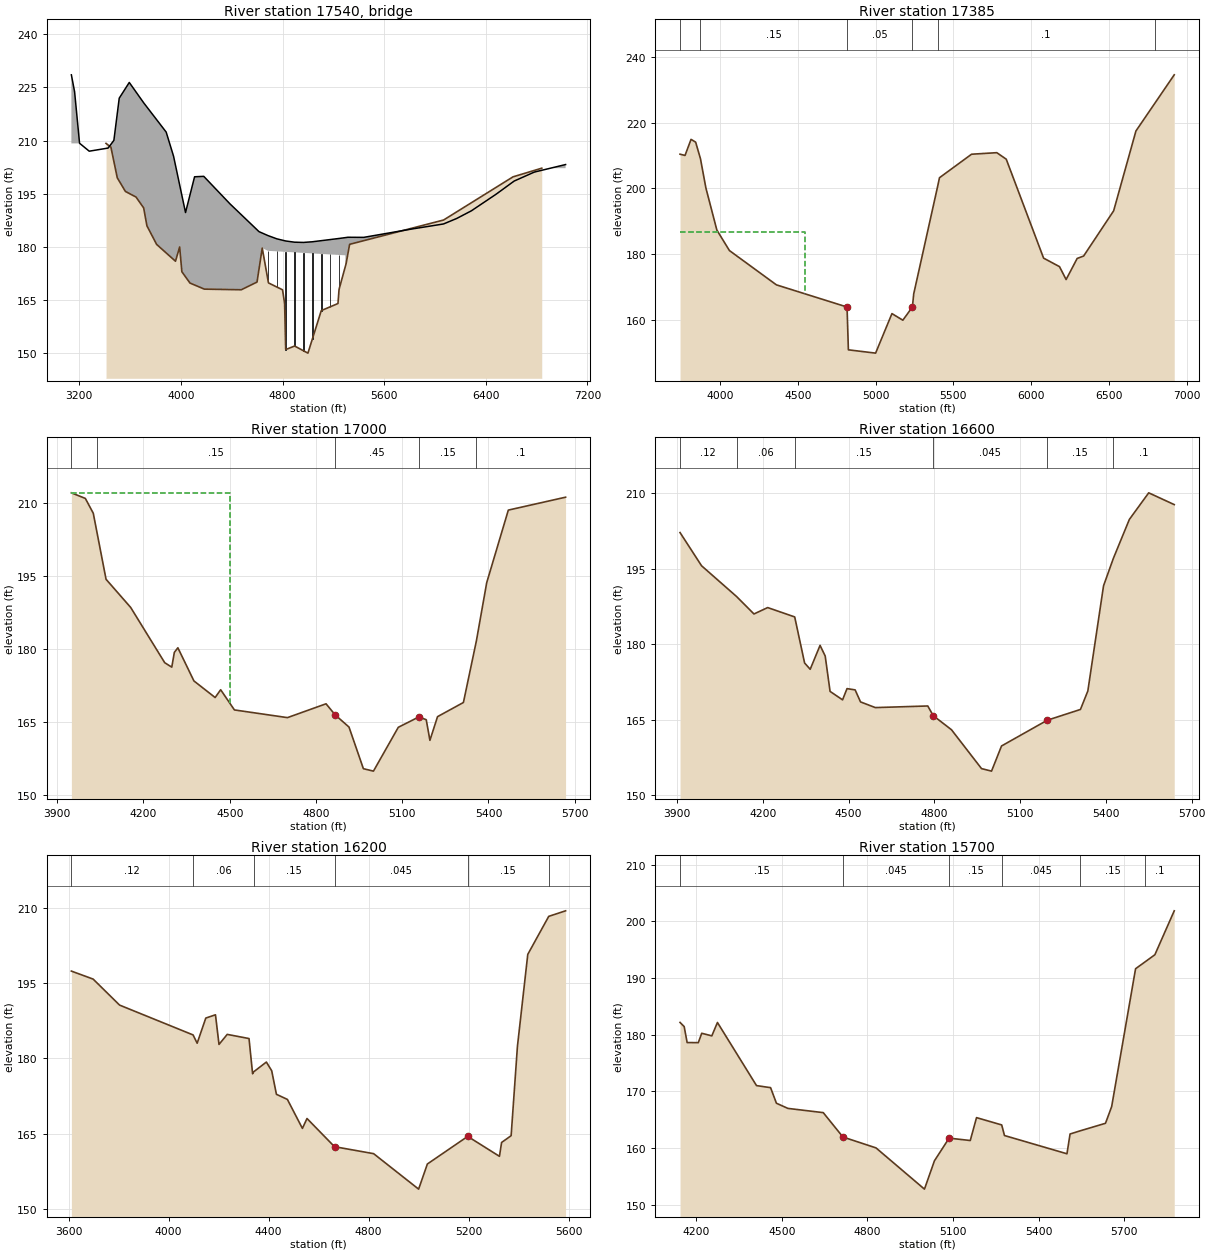
Type RM Length L Ch R =3,17540,,,
BEGIN DESCRIPTION:
SALUDA RIVER (I-26 - TOR)
Structure ID: I-26
Detailed Survey Structure
END DESCRIPTION:
Bridge Culvert--1,0,-1,-1,0
Deck Dist Width WeirC Skew NumUp NumDn MinLoCord MaxHiCord MaxSubmerge Is_Ogee
61.5,127,3,,39,39,,,0.95,0,1,1,,
  3138.1  3163.5  3202.5  3278.6  3427.1  3472.6  3514.7  3593.8  3707.5  3884.3
  3942.5  4036.5  4107.7  4180.1  4387.1  4615.0  4635.0  4635.0  4685.0  4755.0
  4825.0  4895.0  4965.0  5035.0  5105.0  5175.0  5245.0  5295.0  5295.0  5315.0
  5438.9  5814.8  6066.9  6170.9  6286.3  6482.2  6623.1  6781.7  7027.8
  228.54  223.76  209.23  206.99  207.87  210.05  221.95  226.39  220.63  212.38
  205.56  189.68  199.77  199.89  192.10  184.28  183.97  183.97  183.18  182.26
  181.65  181.31  181.24  181.43  181.74  182.05  182.36  182.60  182.60  182.70
  182.67  185.01  186.45  188.00  190.16  194.88  198.56  201.09  203.22
  130.00  130.00  130.00  130.00  130.00  130.00  130.00  130.00  130.00  130.00
  130.00  130.00  130.00  130.00  130.00  130.00  130.00  178.97  178.87  178.72
  178.58  178.43  178.29  178.14  177.99  177.85  177.70  177.60  130.00  130.00
  130.00  130.00  130.00  130.00  130.00  130.00  130.00  130.00  130.00
  3138.1  3163.5  3202.5  3278.6  3427.1  3472.6  3514.7  3593.8  3707.5  3884.3
  3942.5  4036.5  4107.7  4180.1  4387.1  4615.0  4635.0  4635.0  4685.0  4755.0
  4825.0  4895.0  4965.0  5035.0  5105.0  5175.0  5245.0  5295.0  5295.0  5315.0
  5438.9  5814.8  6066.9  6170.9  6286.3  6482.2  6623.1  6781.7  7027.8
  228.54  223.76  209.23  206.99  207.87  210.05  221.95  226.39  220.63  212.38
  205.56  189.68  199.77  199.89  192.10  184.28  183.97  183.97  183.18  182.26
  181.65  181.31  181.24  181.43  181.74  182.05  182.36  182.60  182.60  182.70
  182.67  185.01  186.45  188.00  190.16  194.88  198.56  201.09  203.22
  130.00  130.00  130.00  130.00  130.00  130.00  130.00  130.00  130.00  130.00
  130.00  130.00  130.00  130.00  130.00  130.00  130.00  178.97  178.87  178.72
  178.58  178.43  178.29  178.14  177.99  177.85  177.70  177.60  130.00  130.00
  130.00  130.00  130.00  130.00  130.00  130.00  130.00  130.00  130.00
Pier Skew, UpSta & Num, DnSta & Num=,4685,2,4685,2,0,0,0,0,0
       4       4
  163.50  178.86
       4       4
  163.50  178.86
Pier Skew, UpSta & Num, DnSta & Num=,4755,2,4755,2,0,0,0,0,0
       4       4
  163.00  178.72
       4       4
  163.00  178.72
Pier Skew, UpSta & Num, DnSta & Num=,4825,2,4825,2,0,0,0,0,0
       4       4
  149.00  178.57
       4       4
  149.00  178.57
Pier Skew, UpSta & Num, DnSta & Num=,4895,2,4895,2,0,0,0,0,0
       4       4
  150.00  178.43
       4       4
  150.00  178.43
Pier Skew, UpSta & Num, DnSta & Num=,4965,2,4965,2,0,0,0,0,0
       4       4
  148.50  178.28
       4       4
  148.50  178.28
Pier Skew, UpSta & Num, DnSta & Num=,5035,2,5035,2,0,0,0,0,0
       4       4
  153.00  178.14
       4       4
  153.00  178.14
Pier Skew, UpSta & Num, DnSta & Num=,5105,2,5105,2,0,0,0,0,0
       4       4
  160.00  178.00
       4       4
  160.00  178.00
Pier Skew, UpSta & Num, DnSta & Num=,5175,2,5175,2,0,0,0,0,0
       4       4
  158.00  177.85
       4       4
  158.00  177.85
Pier Skew, UpSta & Num, DnSta & Num=,5245,2,5245,2,0,0,0,0,0
       4       4
  166.00  177.71
       4       4
  166.00  177.71
BR Coef=1,1,0,1.25,0,,,0.8,0,2,0,
WSPro=,,,, 1 ,,,, 0 ,,,, 0 ,,,,-1 ,-1 ,-1 , 0 , 0 , 0 , 0 , 0
BC Design=,,0,,0,,,,,,

Type RM Length L Ch R = 1,17385,306,385,416
BEGIN DESCRIPTION:
SALUDA RIVER (I-26 - DS)
END DESCRIPTION:
XS GIS Cut Line= 3
      1969350.99       798187.76      1968803.81       797056.00
      1968156.70       795248.87
#Sta/Elev= 30
  3742.9  210.41  3774.9  210.03  3813.7  214.91  3843.2  214.07  3874.1  209.05
  3909.0  200.17  3979.5  187.38  4060.3  181.15  4362.4  170.73  4816.4  164.00
  4825.0  151.00  5000.0  150.00  5105.0  162.00  5175.0  160.00  5236.4  164.00
  5245.0  168.00  5399.2  200.73  5410.6  203.27  5616.7  210.40  5778.9  210.87
  5839.7  208.89  6079.7  178.85  6182.0  176.26  6224.5  172.35  6295.6  178.75
  6337.1  179.49  6530.0  193.21  6673.3  217.46  6793.0  225.75  6919.5  234.51
#Mann=6,-1,0
  3742.9    0.06       0  3874.1    0.15       0  4816.4    0.05       0
  5236.4    0.15       0  5399.2     0.1       0  6793.0    0.11       0
#XS Ineff=2,0
    0.00 4543.50  186.69 5386.50    0.00  182.42
Permanent Ineff=
       F       F
Bank Sta=4816.4,5236.4
Exp/Cntr=0.5,0.3

Type RM Length L Ch R = 1,17000,500,400,251
BEGIN DESCRIPTION:
SALUDA RIVER 37.0
END DESCRIPTION:
XS GIS Cut Line= 3
      1969399.20       798164.06      1969175.35       797137.59
      1969019.47       796487.82
#Sta/Elev= 30
  3949.4  212.12  3998.0  210.97  4025.6  207.92  4039.3  203.74  4070.0  194.36
  4155.6  188.58  4274.1  177.22  4298.6  176.31  4307.5  179.34  4319.8  180.29
  4375.6  173.48  4449.4  170.07  4468.6  171.67  4516.5  167.52  4700.9  165.94
  4835.1  168.78  4866.8  166.51  4915.0  164.00  4965.0  155.45  5000.0  154.95
  5086.4  163.95  5158.2  166.09  5183.6  165.51  5196.4  161.28  5222.9  166.14
  5312.9  169.05  5358.1  181.73  5393.9  193.66  5469.1  208.57  5668.2  211.22
#Mann=5,-1,0
  3949.4    0.06       0  4039.3    0.15       0  4866.8    0.45       0
  5158.2    0.15       0  5358.1     0.1       0
#XS Ineff=2,0
    0.00 4500.00  212.00               0
Permanent Ineff=
       F       F
Bank Sta=4866.8,5158.2
Exp/Cntr=0.3,0.1

Type RM Length L Ch R = 1,16600,671,400,215
BEGIN DESCRIPTION:
SALUDA RIVER 36.0
END DESCRIPTION:
XS GIS Cut Line= 3
      1970093.60       797930.83      1969538.96       796992.96
      1969111.71       796517.66
#Sta/Elev= 30
  3910.4  202.20  3985.7  195.60  4107.9  189.50  4169.0  186.02  4217.0  187.29
  4311.5  185.43  4346.1  176.28  4365.7  175.02  4400.2  179.78  4418.2  177.65
  4435.2  170.63  4478.9  168.95  4494.5  171.18  4522.9  170.93  4541.7  168.54
  4593.5  167.41  4776.9  167.73  4796.2  165.80  4860.0  163.00  4965.0  155.28
  5000.0  154.78  5035.0  159.78  5194.6  164.89  5311.0  167.04  5336.9  170.72
  5391.8  191.62  5426.1  197.06  5482.1  204.81  5549.8  210.10  5639.1  207.76
#Mann=6,-1,0
  3910.4    0.12       0  4107.9    0.06       0  4311.5    0.15       0
  4796.2   0.045       0  5194.6    0.15       0  5426.1     0.1       0
Bank Sta=4796.2,5194.6
Exp/Cntr=0.3,0.1

Type RM Length L Ch R = 1,16200,568,500,361
BEGIN DESCRIPTION:
SALUDA RIVER 35.0
END DESCRIPTION:
XS GIS Cut Line= 3
      1971090.43       797146.26      1969782.51       796678.06
      1969215.04       796524.44
#Sta/Elev= 30
  3610.8  197.35  3697.8  195.76  3803.7  190.58  4097.7  184.64  4114.0  182.99
  4148.6  188.00  4187.3  188.65  4201.4  182.75  4234.3  184.75  4321.5  183.92
  4335.8  176.91  4339.7  177.28  4390.9  179.24  4412.2  177.51  4431.1  172.82
  4475.0  171.80  4535.1  166.03  4553.5  168.00  4663.5  162.39  4820.0  161.00
  5000.0  153.94  5035.0  158.94  5196.4  164.44  5323.4  160.47  5331.9  163.23
  5370.1  164.58  5395.3  182.36  5436.7  200.68  5520.6  208.25  5587.9  209.35
#Mann=6,-1,0
  3610.8    0.12       0  4097.7    0.06       0  4339.7    0.15       0
  4663.5   0.045       0  5196.4    0.15       0  5520.6     0.1       0
Bank Sta=4663.5,5196.4
Exp/Cntr=0.3,0.1

Type RM Length L Ch R = 1,15700,479,500,875
BEGIN DESCRIPTION:
SALUDA RIVER 34.0
END DESCRIPTION:
XS GIS Cut Line= 3
      1970790.53       796347.75      1969944.34       796211.38
      1969069.45       796253.32
#Sta/Elev= 30
  4142.9  182.14  4157.4  181.41  4167.8  178.59  4206.9  178.57  4219.0  180.23
  4254.3  179.77  4274.1  182.13  4411.1  170.99  4460.4  170.63  4480.9  167.88
  4521.0  166.97  4645.1  166.22  4714.1  161.92  4830.0  160.00  5000.0  152.72
  5035.0  157.72  5086.4  161.72  5160.6  161.30  5182.6  165.34  5270.9  164.05
  5280.6  162.18  5499.7  158.96  5510.6  162.45  5546.1  163.01  5634.8  164.34
  5656.4  167.27  5740.3  191.62  5773.3  192.82  5808.0  194.09  5875.9  201.84
#Mann=6,-1,0
  4142.9    0.15       0  4714.1   0.045       0  5086.4    0.15       0
  5270.9   0.045       0  5546.1    0.15       0  5773.3     0.1       0
Bank Sta=4714.1,5086.4
Exp/Cntr=0.3,0.1

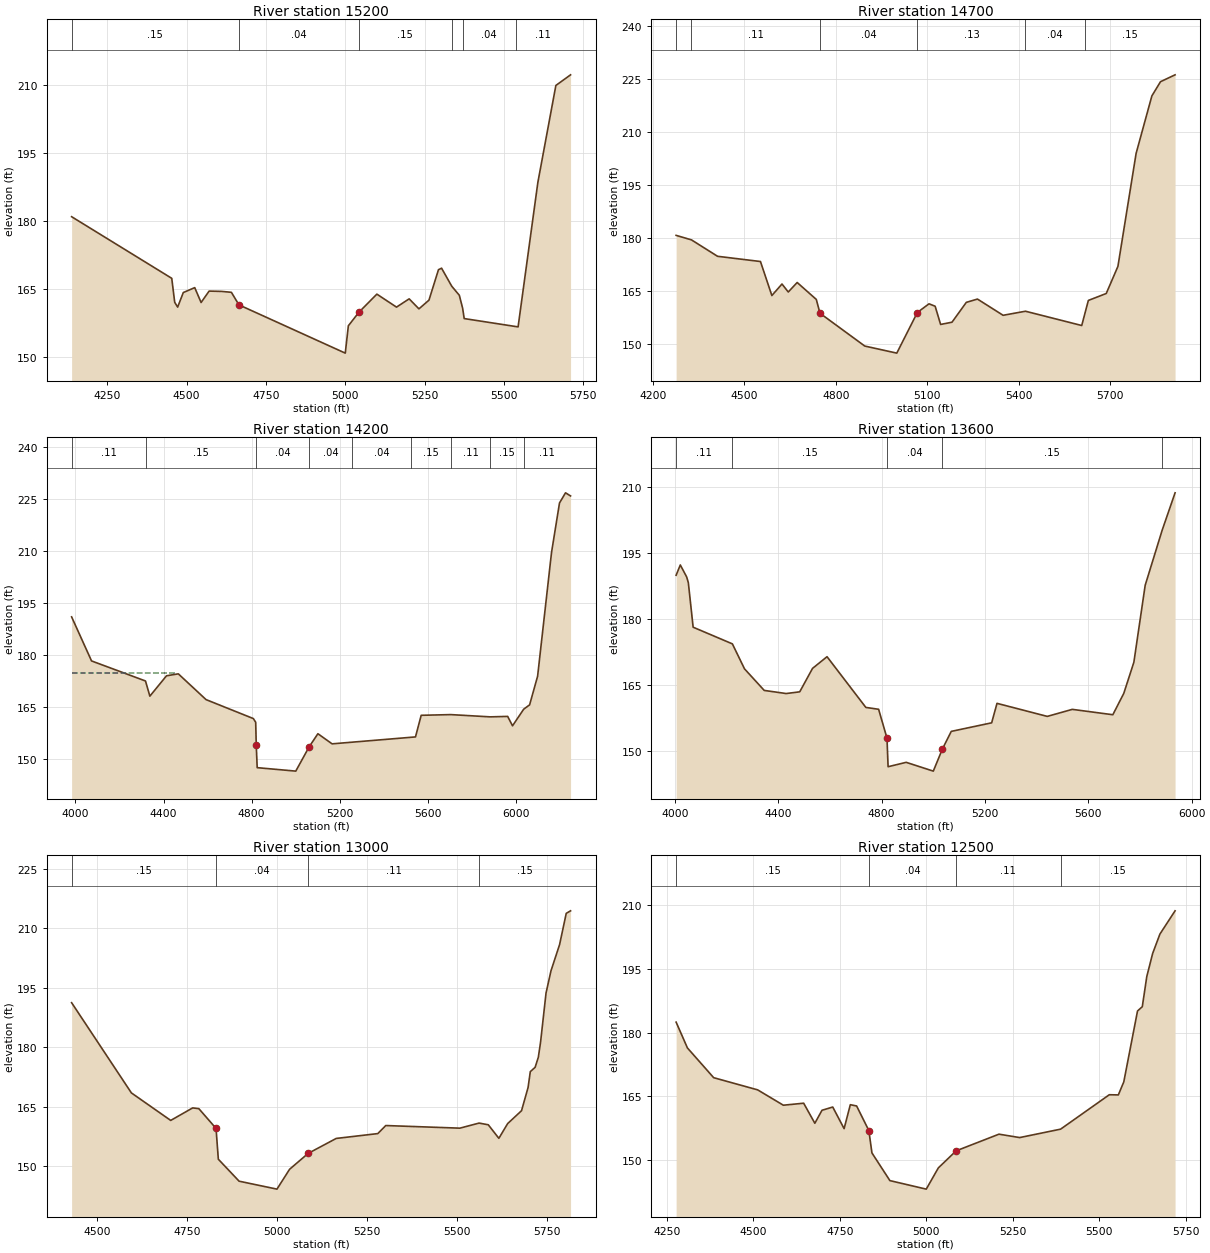
Type RM Length L Ch R = 1,15200,373,500,257
BEGIN DESCRIPTION:
SALUDA RIVER 33.0
END DESCRIPTION:
XS GIS Cut Line= 3
      1970772.22       795887.77      1969927.54       795712.40
      1969279.56       795421.69
#Sta/Elev= 30
  4137.3  180.98  4453.0  167.41  4462.3  162.13  4471.6  161.07  4489.4  164.28
  4525.4  165.36  4545.5  162.09  4570.8  164.60  4610.8  164.53  4641.0  164.33
  4664.7  161.57  5000.0  150.94  5009.7  156.96  5043.0  159.94  5099.6  163.93
  5161.5  161.07  5201.4  162.89  5232.2  160.69  5263.8  162.60  5293.8  169.31
  5303.6  169.64  5335.6  165.68  5359.6  163.67  5370.0  160.81  5374.9  158.55
  5537.0  156.80  5544.8  156.72  5607.1  188.53  5663.9  209.88  5710.2  212.22
#Mann=6,-1,0
  4137.3    0.15       0  4664.7    0.04       0  5043.0    0.15       0
  5335.6    0.11       0  5370.0    0.04       0  5537.0    0.11       0
Bank Sta=4664.7,5043
Exp/Cntr=0.3,0.1

Type RM Length L Ch R = 1,14700,508,500,394
BEGIN DESCRIPTION:
SALUDA RIVER 32.0
END DESCRIPTION:
XS GIS Cut Line= 3
      1970827.10       795644.10      1970173.87       795332.59
      1969267.43       795226.75
#Sta/Elev= 30
  4276.3  180.81  4326.7  179.53  4412.2  174.89  4552.9  173.41  4590.3  163.79
  4623.5  167.05  4644.1  164.79  4673.3  167.48  4736.0  162.69  4748.1  158.78
  4895.0  149.50  5000.0  147.50  5067.4  158.99  5105.6  161.45  5125.8  160.76
  5143.7  155.61  5181.1  156.25  5228.0  161.86  5264.6  162.79  5348.6  158.20
  5422.0  159.35  5606.5  155.31  5616.8  158.68  5628.2  162.40  5686.9  164.37
  5725.2  172.04  5784.8  203.98  5836.5  220.25  5864.8  224.27  5912.6  226.22
#Mann=6,-1,0
  4276.3    0.15       0  4326.7    0.11       0  4748.1    0.04       0
  5067.4    0.13       0  5422.0    0.04       0  5616.8    0.15       0
Bank Sta=4748.1,5067.4
Exp/Cntr=0.3,0.1

Type RM Length L Ch R = 1,14200,494,600,1335
BEGIN DESCRIPTION:
SALUDA RIVER 31.0
END DESCRIPTION:
XS GIS Cut Line= 3
      1971321.04       795296.85      1970388.47       794891.38
      1969142.49       794852.07
#Sta/Elev= 30
  3983.1  190.99  4073.5  178.29  4318.3  172.51  4338.1  168.14  4413.6  174.01
  4467.2  174.57  4593.0  167.14  4807.5  161.68  4818.2  160.61  4820.7  154.03
  4825.0  147.53  5000.0  146.53  5060.7  153.53  5100.4  157.31  5164.8  154.39
  5256.7  154.88  5522.6  156.28  5543.1  156.39  5569.0  162.62  5703.4  162.82
  5881.9  162.17  5961.3  162.30  5983.3  159.59  6034.0  164.38  6060.8  165.63
  6097.1  173.88  6160.2  209.53  6196.4  223.81  6223.7  226.74  6246.6  225.84
#Mann=9,-1,0
  3983.1    0.11       0  4318.3    0.15       0  4820.7    0.04       0
  5060.7    0.04       0  5256.7    0.04       0  5522.6    0.15       0
  5703.4    0.11       0  5881.9    0.15       0  6034.0    0.11       0
#XS Ineff=2,0
    0.00 4450.00  174.70               0
Permanent Ineff=
       F       F
Bank Sta=4820.7,5060.7
Exp/Cntr=0.3,0.1

Type RM Length L Ch R = 1,13600,580,600,593
BEGIN DESCRIPTION:
SALUDA RIVER 30.0
END DESCRIPTION:
XS GIS Cut Line= 3
      1971368.80       795193.44      1970749.15       794414.17
      1970242.17       793627.48
#Sta/Elev= 30
  4004.4  189.92  4020.6  192.26  4045.2  189.54  4051.7  188.23  4070.3  178.10
  4222.2  174.31  4269.1  168.63  4345.5  163.72  4430.4  163.01  4482.9  163.40
  4532.5  168.73  4588.6  171.39  4738.9  159.85  4788.3  159.43  4820.7  152.86
  4825.0  146.36  4895.0  147.36  5000.0  145.36  5035.0  150.36  5069.5  154.40
  5225.9  156.35  5246.6  160.78  5441.2  157.81  5538.0  159.41  5695.0  158.19
  5737.3  163.04  5776.4  170.13  5820.2  187.64  5885.9  200.16  5935.9  208.67
#Mann=5,-1,0
  4004.4    0.11       0  4222.2    0.15       0  4820.7    0.04       0
  5035.0    0.15       0  5885.9    0.12       0
Bank Sta=4820.7,5035
Exp/Cntr=0.3,0.1

Type RM Length L Ch R = 1,13000,486,500,423
BEGIN DESCRIPTION:
SALUDA RIVER 29.0
END DESCRIPTION:
XS GIS Cut Line= 3
      1971558.15       794559.65      1971247.65       794082.11
      1970790.48       793408.14
#Sta/Elev= 30
  4430.4  191.19  4596.2  168.45  4705.3  161.51  4766.3  164.67  4783.4  164.47
  4831.0  159.50  4837.4  151.73  4895.0  146.19  5000.0  144.19  5035.0  149.19
  5086.4  153.19  5164.4  156.97  5279.7  158.19  5301.8  160.22  5507.4  159.56
  5560.6  160.84  5586.2  160.41  5615.5  157.00  5639.9  160.71  5678.4  163.96
  5696.6  169.83  5702.7  173.80  5716.1  174.90  5725.0  177.43  5731.2  181.24
  5746.4  193.64  5760.1  199.23  5783.9  205.82  5802.4  213.71  5814.4  214.35
#Mann=4,-1,0
  4430.4    0.15       0  4831.0    0.04       0  5086.4    0.11       0
  5560.6    0.15       0
Bank Sta=4831,5086.4
Exp/Cntr=0.3,0.1

Type RM Length L Ch R = 1,12500,455,500,763
BEGIN DESCRIPTION:
SALUDA RIVER 28.0
END DESCRIPTION:
XS GIS Cut Line= 3
      1972005.95       794401.26      1971642.46       793776.63
      1971146.88       793255.84
#Sta/Elev= 30
  4277.3  182.48  4310.0  176.41  4385.8  169.42  4512.8  166.56  4587.1  162.95
  4645.8  163.42  4678.1  158.71  4698.8  161.76  4729.8  162.52  4762.7  157.44
  4780.6  163.07  4798.8  162.77  4834.1  157.00  4843.1  151.73  4895.0  145.22
  5000.0  143.22  5035.0  148.22  5086.4  152.22  5210.1  156.14  5269.9  155.34
  5388.2  157.32  5528.9  165.41  5555.0  165.37  5570.7  168.42  5610.4  185.10
  5624.2  186.11  5637.2  193.21  5654.1  198.62  5675.1  203.18  5718.9  208.65
#Mann=4,-1,0
  4277.3    0.15       0  4834.1    0.04       0  5086.4    0.11       0
  5388.2    0.15       0
Bank Sta=4834.1,5086.4
Exp/Cntr=0.3,0.1

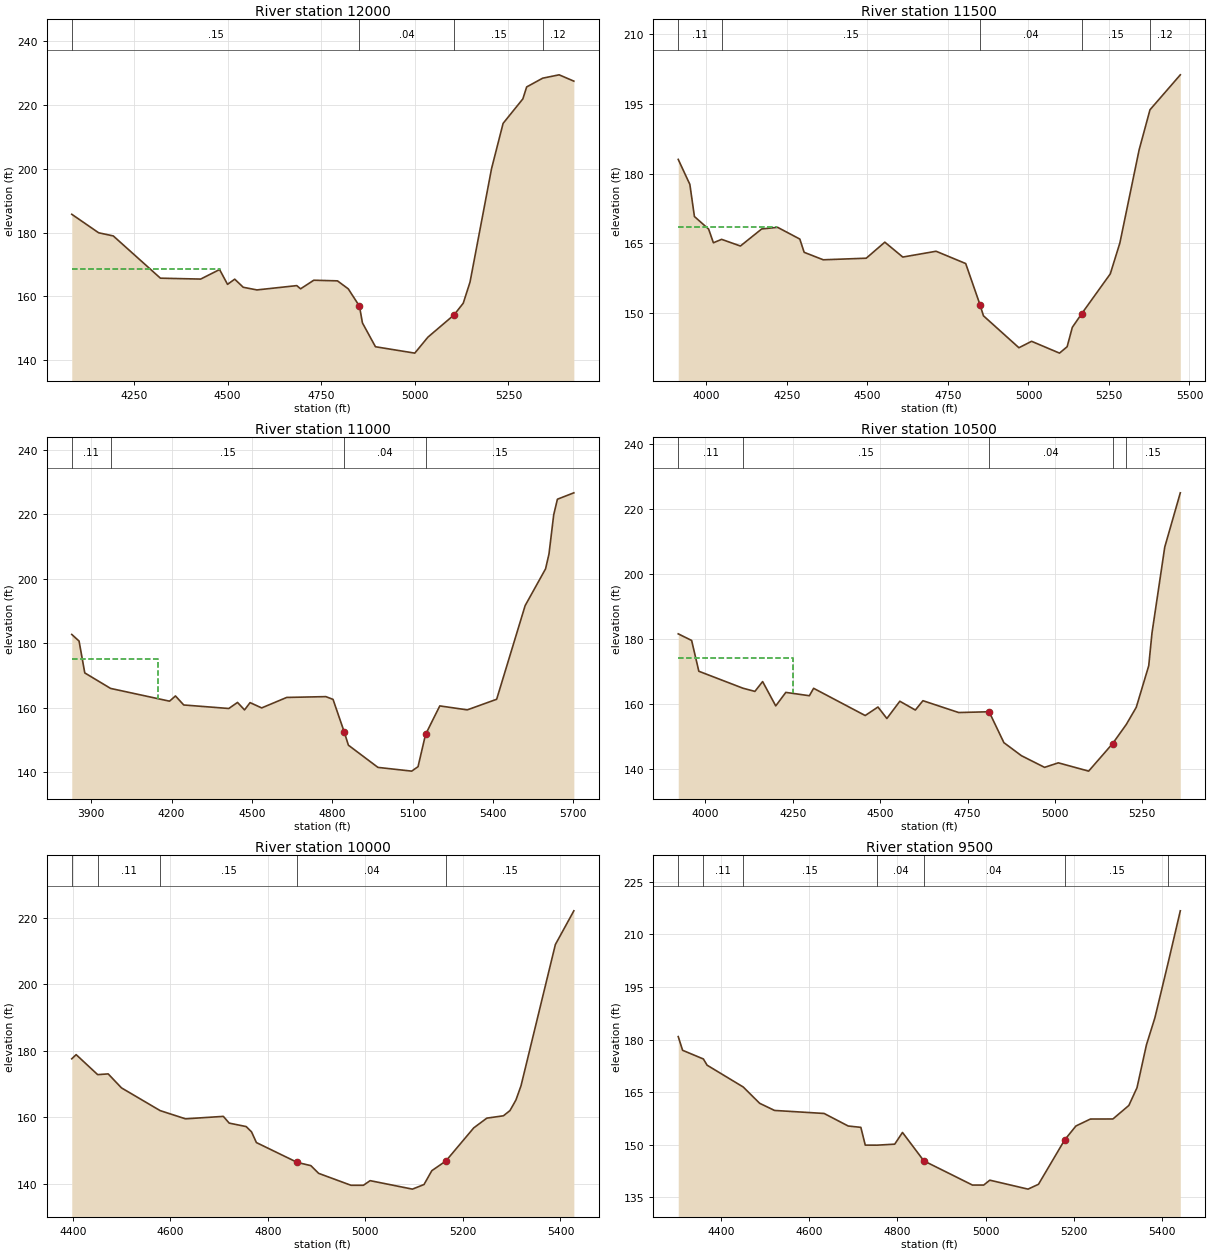
Type RM Length L Ch R = 1,12000,505,500,406
BEGIN DESCRIPTION:
SALUDA RIVER 27.0
END DESCRIPTION:
XS GIS Cut Line= 3
      1972386.71       794416.48      1972085.09       793551.67
      1971917.58       793161.40
#Sta/Elev= 30
  4084.1  185.77  4155.9  179.97  4195.0  178.98  4320.8  165.74  4428.3  165.46
  4478.8  168.45  4500.0  163.81  4519.2  165.43  4542.0  162.89  4578.5  162.06
  4684.8  163.41  4695.1  162.41  4730.3  165.10  4793.6  164.90  4822.5  162.38
  4852.3  156.96  4860.2  151.73  4895.0  144.25  5000.0  142.25  5035.0  147.25
  5105.0  154.25  5129.4  157.90  5147.5  164.52  5205.0  200.10  5235.8  214.26
  5288.6  221.94  5298.7  225.68  5341.5  228.43  5385.4  229.48  5424.7  227.50
#Mann=4,-1,0
  4084.1    0.15       0  4852.3    0.04       0  5105.0    0.15       0
  5341.5    0.12       0
#XS Ineff=2,0
    0.00 4480.00  168.70               0
Permanent Ineff=
       F       F
Bank Sta=4852.3,5105
Exp/Cntr=0.3,0.1

Type RM Length L Ch R = 1,11500,384,500,897
BEGIN DESCRIPTION:
SALUDA RIVER 26.0
END DESCRIPTION:
XS GIS Cut Line= 3
      1972936.22       794374.07      1972543.94       793359.57
      1972176.50       793063.94
#Sta/Elev= 30
  3912.3  183.05  3948.4  177.66  3962.6  170.73  4006.8  168.01  4021.5  165.07
  4047.0  165.81  4105.4  164.37  4171.5  168.05  4221.0  168.40  4289.9  165.87
  4303.4  163.01  4362.7  161.40  4496.2  161.74  4553.9  165.20  4609.7  161.99
  4713.1  163.24  4805.1  160.59  4849.4  151.73  4860.2  149.32  4970.4  142.43
  5009.7  143.82  5096.4  141.27  5120.1  142.65  5136.2  146.83  5165.0  149.74
  5254.1  158.36  5283.9  165.03  5343.6  185.08  5377.4  193.75  5471.6  201.29
#Mann=5,-1,0
  3912.3    0.11       0  4047.0    0.15       0  4849.4    0.04       0
  5165.0    0.15       0  5377.4    0.12       0
#XS Ineff=2,0
    0.00 4220.00  168.42               0
Permanent Ineff=
       F       F
Bank Sta=4849.4,5165
Exp/Cntr=0.3,0.1

Type RM Length L Ch R = 1,11000,398,500,523
BEGIN DESCRIPTION:
SALUDA RIVER 25.0
END DESCRIPTION:
XS GIS Cut Line= 3
      1972975.80       794356.93      1973004.91       793184.99
      1973233.56       792521.69
#Sta/Elev= 30
  3827.7  182.72  3854.9  180.67  3876.3  170.78  3972.5  165.97  4192.6  162.01
  4214.7  163.63  4245.6  160.83  4413.8  159.74  4446.3  161.62  4472.5  159.30
  4493.2  161.56  4536.5  159.92  4630.0  163.17  4776.0  163.42  4802.8  162.57
  4844.6  152.46  4860.2  148.35  4970.4  141.46  5096.4  140.30  5120.1  141.68
  5148.1  151.67  5201.3  160.54  5303.9  159.31  5413.5  162.60  5519.8  191.66
  5596.0  203.07  5608.8  207.69  5626.5  219.87  5640.3  224.69  5701.6  226.67
#Mann=4,-1,0
  3827.7    0.11       0  3972.5    0.15       0  4844.6    0.04       0
  5148.1    0.15       0
#XS Ineff=2,0
    0.00 4150.00  175.00               0
Permanent Ineff=
       F       F
Bank Sta=4844.6,5148.1
Exp/Cntr=0.3,0.1

Type RM Length L Ch R = 1,10500,779,500,198
BEGIN DESCRIPTION:
SALUDA RIVER 24.0
END DESCRIPTION:
XS GIS Cut Line= 3
      1973092.90       794313.93      1973478.94       793308.39
      1973639.32       792987.76
#Sta/Elev= 30
  3922.9  181.53  3961.2  179.50  3981.8  170.03  4107.9  164.82  4142.1  163.84
  4164.2  166.86  4201.7  159.38  4230.5  163.53  4297.9  162.51  4310.0  164.79
  4457.5  156.42  4494.0  159.04  4519.5  155.51  4556.5  160.81  4600.9  158.11
  4622.6  160.98  4724.8  157.34  4811.8  157.58  4854.1  148.08  4904.1  144.08
  4970.4  140.49  5009.7  141.88  5096.4  139.33  5165.0  147.80  5203.9  153.65
  5232.6  158.96  5268.2  171.72  5277.5  181.76  5314.0  208.19  5358.5  224.88
#Mann=5,-1,0
  3922.9    0.11       0  4107.9    0.15       0  4811.8    0.04       0
  5165.0    0.15       0  5203.9    0.15       0
#XS Ineff=2,0
    0.00 4250.00  174.00               0
Permanent Ineff=
       F       F
Bank Sta=4811.8,5165
Exp/Cntr=0.3,0.1

Type RM Length L Ch R = 1,10000,530,500,501
BEGIN DESCRIPTION:
SALUDA RIVER 23.0
END DESCRIPTION:
XS GIS Cut Line= 3
      1974218.09       793859.03      1973948.16       793320.82
      1973672.84       792993.92
#Sta/Elev= 30
  4397.9  177.61  4406.9  178.86  4451.0  172.84  4472.6  173.06  4499.8  168.85
  4579.2  162.00  4631.1  159.53  4708.7  160.27  4720.7  158.24  4755.5  157.20
  4766.5  155.61  4776.5  152.38  4860.2  146.41  4888.2  145.43  4904.1  143.11
  4970.4  139.52  4995.9  139.52  5009.7  140.91  5096.4  138.36  5120.1  139.74
  5136.2  143.92  5165.0  146.83  5222.1  156.80  5249.0  159.74  5282.9  160.44
  5296.4  162.01  5308.7  165.22  5319.1  169.50  5389.5  212.01  5427.4  222.17
#Mann=5,-1,0
  4397.9    0.06       0  4451.0    0.11       0  4579.2    0.15       0
  4860.2    0.04       0  5165.0    0.15       0
Bank Sta=4860.2,5165
Exp/Cntr=0.3,0.1

Type RM Length L Ch R = 1,9500,484,500,500
BEGIN DESCRIPTION:
SALUDA RIVER 22.0
END DESCRIPTION:
XS GIS Cut Line= 3
      1974714.62       793590.97      1974335.50       793006.34
      1974044.47       792674.07
#Sta/Elev= 30
  4303.2  180.84  4313.1  176.94  4360.3  174.46  4368.6  172.70  4450.6  166.48
  4487.8  161.84  4521.6  159.80  4634.0  158.94  4688.5  155.37  4717.3  154.98
  4727.3  149.92  4754.1  149.91  4794.1  150.19  4811.7  153.53  4860.2  145.43
  4970.4  138.54  4995.9  138.54  5009.7  139.93  5096.4  137.38  5120.1  138.76
  5179.5  151.41  5205.0  155.37  5237.8  157.35  5288.9  157.37  5325.0  161.22
  5343.5  166.28  5364.9  178.50  5384.1  186.22  5414.0  201.83  5441.7  216.68
#Mann=7,-1,0
  4303.2    0.06       0  4360.3    0.11       0  4450.6    0.15       0
  4754.1    0.04       0  4860.2    0.04       0  5179.5    0.15       0
  5414.0    0.12       0
Bank Sta=4860.2,5179.5
Exp/Cntr=0.3,0.1