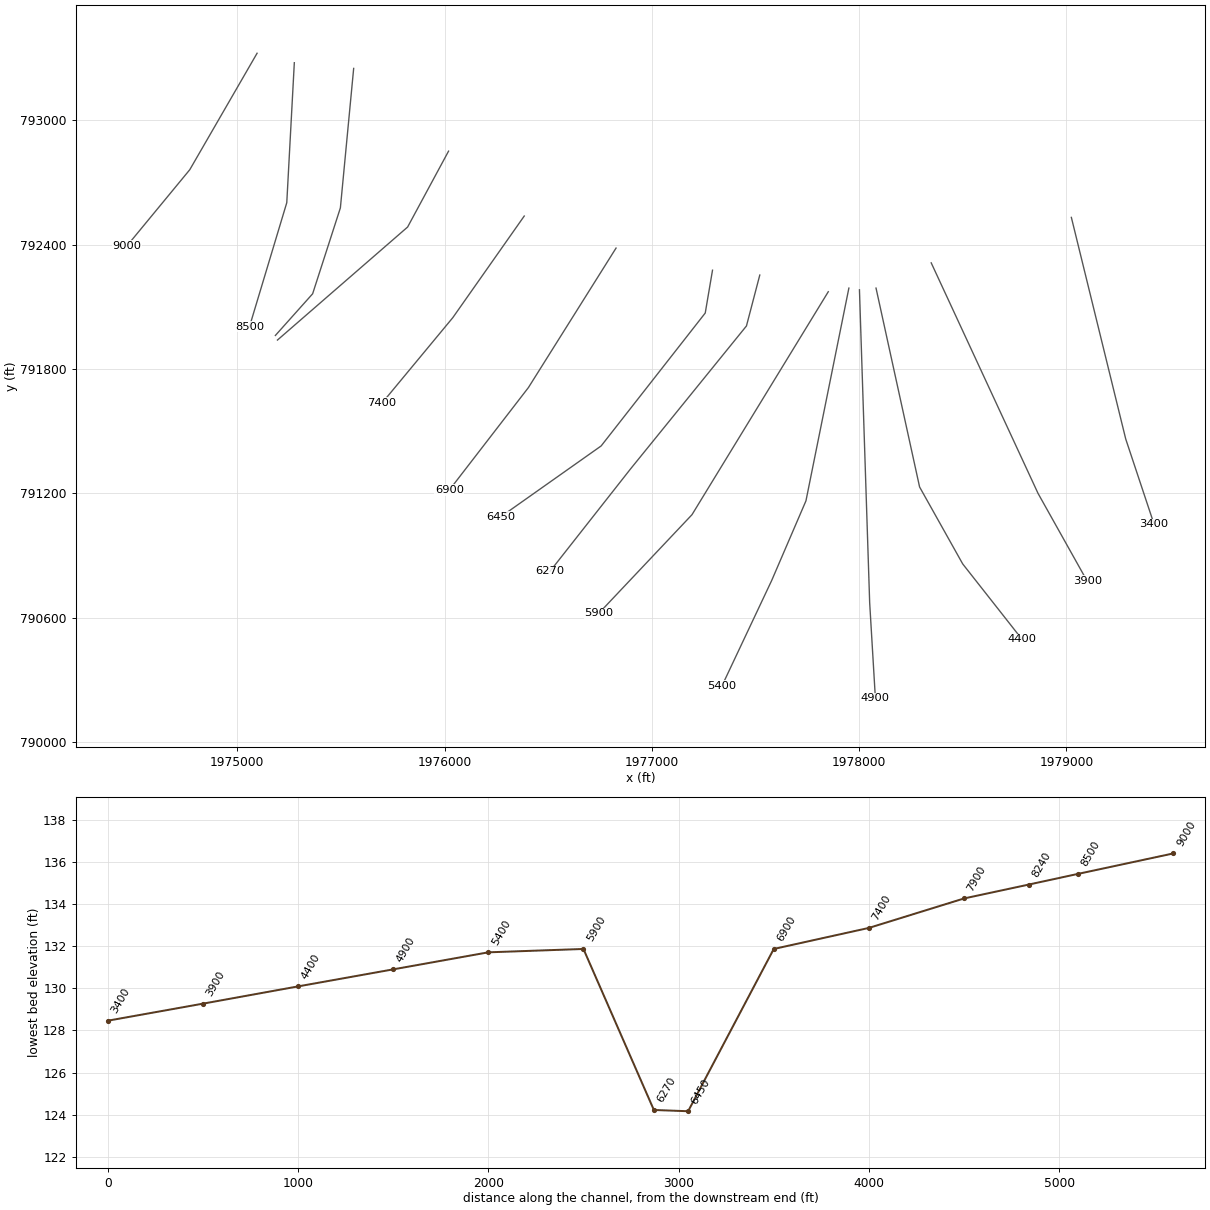
HEC-RAS study SALUDA RIVER.prj: SALUDA RIVER Detailed Study

--- SALUDA RIVER.g01 (geometry) --- (continued)

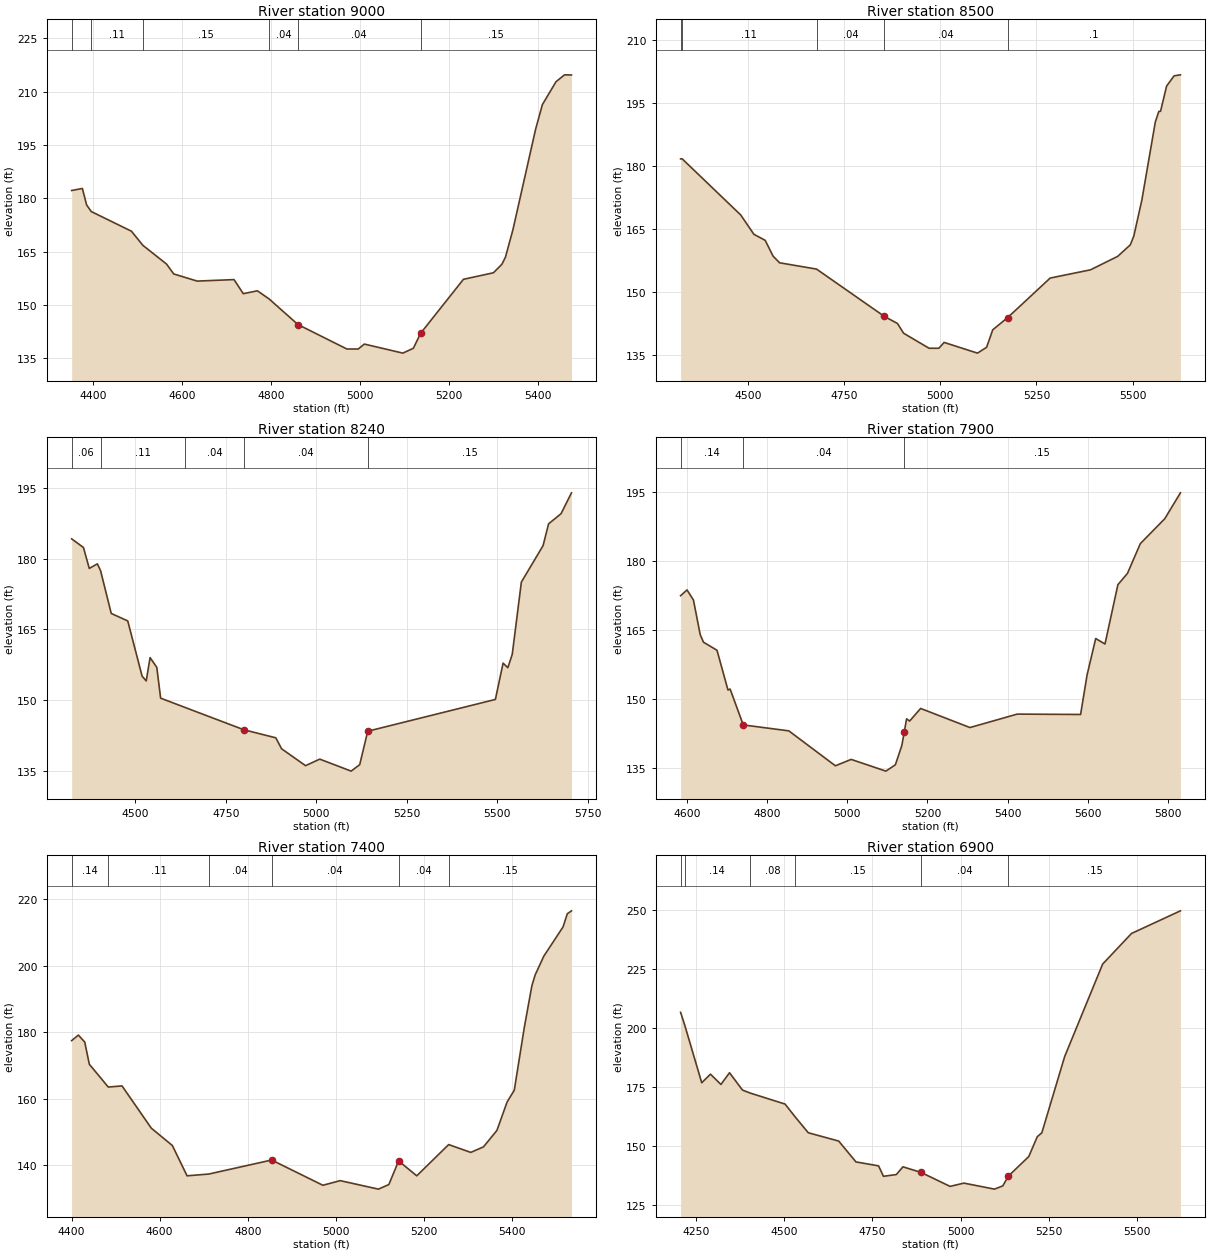
Type RM Length L Ch R = 1,9000,299,500,620
BEGIN DESCRIPTION:
SALUDA RIVER 21.0
END DESCRIPTION:
XS GIS Cut Line= 3
      1975095.40       793322.92      1974770.61       792760.92
      1974467.84       792393.76
#Sta/Elev= 30
  4350.9  182.19  4375.0  182.77  4384.6  178.12  4395.0  176.27  4485.4  170.74
  4511.3  166.75  4564.5  161.48  4580.6  158.71  4633.3  156.69  4716.4  157.11
  4737.2  153.15  4769.0  153.95  4795.2  151.68  4860.2  144.46  4970.4  137.57
  4995.9  137.57  5009.7  138.96  5096.4  136.41  5120.1  137.79  5136.2  141.97
  5232.7  157.19  5300.2  159.03  5319.4  161.45  5327.3  163.44  5344.2  171.20
  5395.1  199.41  5410.4  206.37  5441.1  212.82  5460.3  214.76  5475.9  214.71
#Mann=6,-1,0
  4350.9    0.06       0  4395.0    0.11       0  4511.3    0.15       0
  4795.2    0.04       0  4860.2    0.04       0  5136.2    0.15       0
Bank Sta=4860.2,5136.2
Exp/Cntr=0.3,0.1

Type RM Length L Ch R = 1,8500,278,260,299
BEGIN DESCRIPTION:
SALUDA RIVER 20.0
END DESCRIPTION:
XS GIS Cut Line= 3
      1975275.11       793277.21      1975238.69       792601.99
      1975058.82       792003.85
#Sta/Elev= 30
  4323.8  181.73  4327.9  181.75  4480.3  168.37  4514.6  163.76  4544.0  162.32
  4564.5  158.56  4581.4  156.97  4677.6  155.47  4854.1  144.19  4888.2  142.51
  4904.1  140.19  4970.4  136.60  4995.9  136.60  5009.7  137.99  5096.4  135.44
  5120.1  136.82  5136.2  141.00  5175.0  143.91  5285.6  153.33  5390.5  155.29
  5461.3  158.50  5494.2  161.25  5503.3  163.35  5524.2  171.90  5559.2  190.50
  5568.4  193.04  5572.9  193.09  5588.6  199.08  5608.1  201.53  5624.6  201.77
#Mann=5,-1,0
  4323.8    0.06       0  4327.9    0.11       0  4677.6    0.04       0
  4854.1    0.04       0  5175.0     0.1       0
Bank Sta=4854.1,5175
Exp/Cntr=0.3,0.1

Type RM Length L Ch R = 1,8240,506,340,167
BEGIN DESCRIPTION:
SALUDA RIVER 19.0
END DESCRIPTION:
XS GIS Cut Line= 4
      1975561.45       793249.76      1975497.34       792576.80
      1975363.45       792162.28      1975183.71       791961.22
#Sta/Elev= 30
  4324.0  184.24  4356.6  182.41  4372.7  177.96  4395.0  178.93  4403.9  177.49
  4433.4  168.40  4479.0  166.82  4518.7  155.09  4530.1  154.08  4540.7  159.03
  4559.3  156.96  4569.9  150.42  4637.3  148.45  4800.0  143.71  4888.2  142.00
  4904.1  139.68  4970.4  136.09  5009.7  137.48  5096.4  134.93  5120.1  136.31
  5142.2  143.40  5495.0  150.15  5516.3  157.86  5529.4  156.89  5541.6  159.72
  5566.8  175.06  5626.8  182.80  5642.0  187.43  5676.4  189.57  5705.3  194.01
#Mann=5,-1,0
  4324.0    0.06       0  4403.9    0.11       0  4637.3    0.04       0
  4800.0    0.04       0  5142.2    0.15       0
Bank Sta=4800,5142.2
Exp/Cntr=0.3,0.1

Type RM Length L Ch R = 1,7900,486,500,550
BEGIN DESCRIPTION:
SALUDA RIVER 18.0
END DESCRIPTION:
XS GIS Cut Line= 3
      1976019.28       792850.52      1975821.70       792484.31
      1975193.71       791939.01
#Sta/Elev= 30
  4583.9  172.39  4599.9  173.64  4616.0  171.45  4632.8  163.95  4641.1  162.28
  4674.8  160.53  4702.2  151.89  4707.5  152.11  4740.3  144.31  4854.1  143.02
  4970.4  135.43  5009.7  136.82  5096.4  134.27  5120.1  135.65  5136.2  139.83
  5142.2  142.74  5148.1  145.64  5155.7  145.15  5183.1  147.89  5306.3  143.74
  5424.3  146.66  5582.5  146.58  5598.6  155.14  5620.2  163.08  5643.4  161.89
  5675.6  174.78  5699.5  177.24  5731.6  183.70  5792.8  189.13  5831.7  194.74
#Mann=3,-1,0
  4583.9    0.14       0  4740.3    0.04       0  5142.2    0.15       0
Bank Sta=4740.3,5142.2
Exp/Cntr=0.3,0.1

Type RM Length L Ch R = 1,7400,509,500,521
BEGIN DESCRIPTION:
SALUDA RIVER 17.0
END DESCRIPTION:
XS GIS Cut Line= 3
      1976384.47       792537.43      1976039.57       792046.83
      1975698.52       791635.28
#Sta/Elev= 30
  4400.3  177.51  4415.6  179.17  4430.0  177.07  4440.4  170.41  4483.4  163.55
  4514.6  163.89  4581.0  151.20  4628.8  145.98  4662.2  136.87  4711.4  137.40
  4854.1  141.62  4970.4  134.03  5009.7  135.42  5096.4  132.87  5120.1  134.25
  5142.2  141.34  5183.4  136.87  5255.8  146.26  5306.0  143.91  5334.7  145.56
  5365.3  150.51  5388.3  159.03  5404.7  162.60  5427.4  181.42  5444.6  193.98
  5452.2  197.29  5471.8  202.91  5515.4  211.69  5525.0  215.63  5534.5  216.52
#Mann=6,-1,0
  4400.3    0.14       0  4483.4    0.11       0  4711.4    0.04       0
  4854.1    0.04       0  5142.2    0.04       0  5255.8    0.15       0
Bank Sta=4854.1,5142.2
Exp/Cntr=0.3,0.1

Type RM Length L Ch R = 1,6900,479,450,378
BEGIN DESCRIPTION:
SALUDA RIVER 16.0
END DESCRIPTION:
XS GIS Cut Line= 3
      1976827.42       792382.79      1976404.69       791709.85
      1976023.24       791215.51
#Sta/Elev= 30
  4205.3  206.79  4216.6  201.60  4265.3  176.95  4290.1  180.60  4319.8  176.24
  4344.2  181.20  4381.0  173.86  4402.2  172.62  4501.9  167.92  4529.7  162.65
  4567.8  155.76  4654.2  152.24  4703.2  143.40  4767.4  141.73  4781.2  137.31
  4817.8  138.04  4836.6  141.33  4888.2  138.94  4970.4  133.03  5009.7  134.42
  5096.4  131.87  5120.1  133.25  5136.2  137.43  5193.9  145.69  5218.0  154.11
  5230.9  155.74  5295.8  188.07  5403.6  227.25  5485.5  240.22  5624.4  249.82
#Mann=6,-1,0
  4205.3    0.06       0  4216.6    0.14       0  4402.2    0.08       0
  4529.7    0.15       0  4888.2    0.04       0  5136.2    0.15       0
Bank Sta=4888.2,5136.2
Exp/Cntr=0.5,0.3

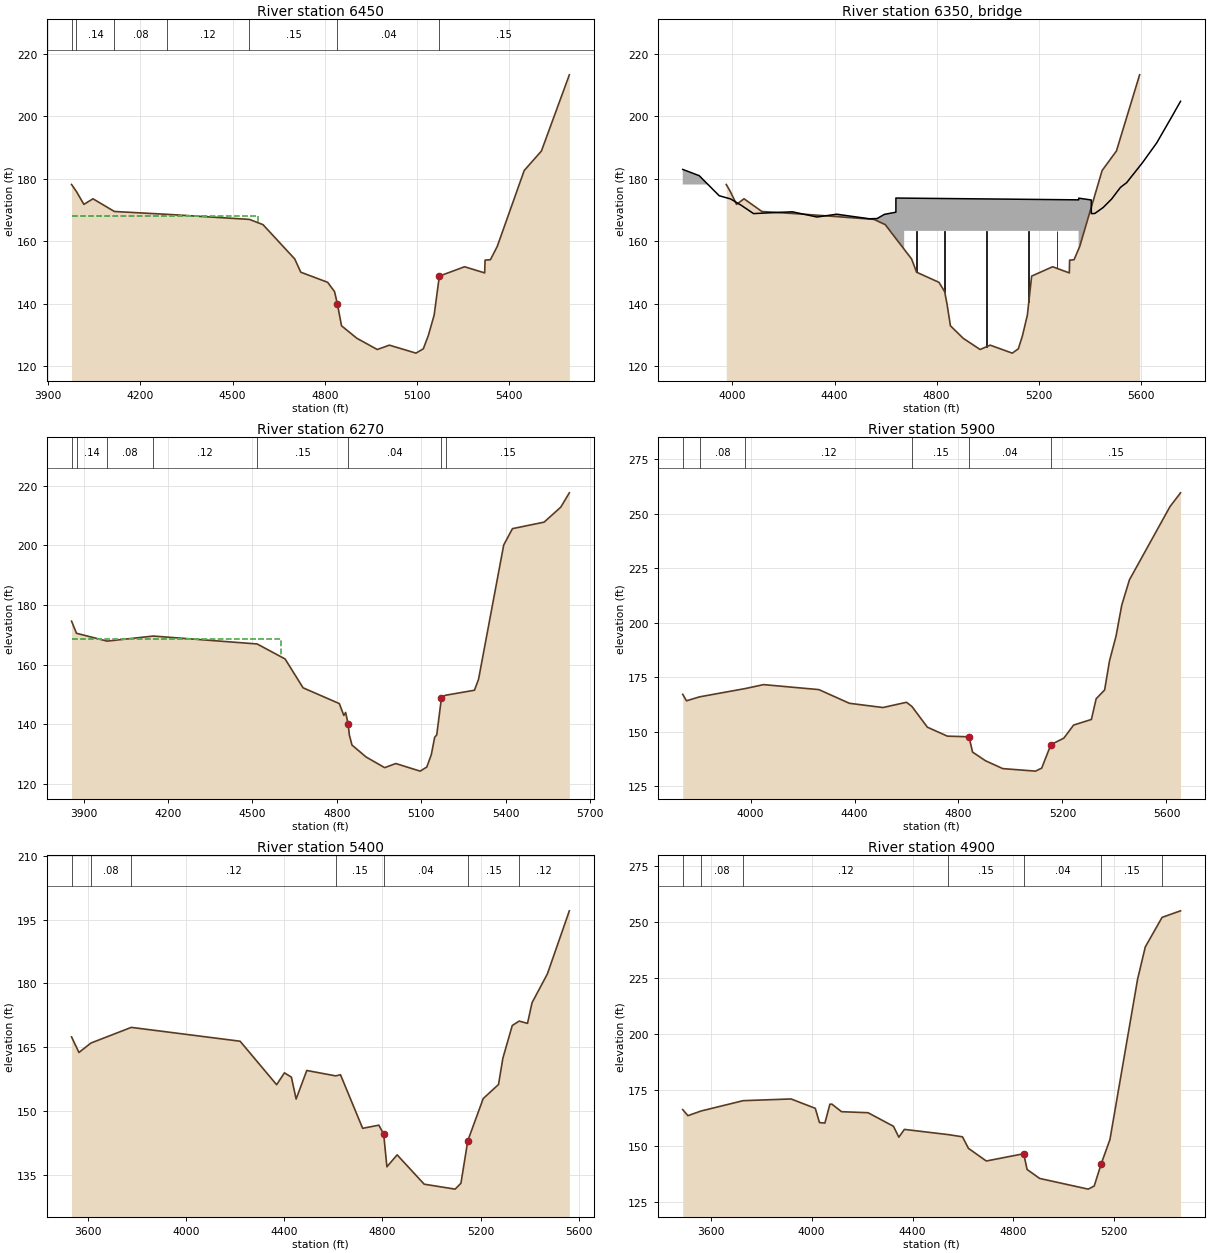
Type RM Length L Ch R = 1,6450,187,180,256
BEGIN DESCRIPTION:
SALUDA RIVER (Riverbanks Zoo - US)
END DESCRIPTION:
XS GIS Cut Line= 4
      1977292.90       792276.08      1977257.81       792069.43
      1976755.63       791428.17      1976269.39       791084.91
#Sta/Elev= 30
  3975.9  178.14  3991.4  175.95  4016.1  171.78  4045.5  173.57  4115.4  169.50
  4285.1  168.60  4554.6  166.97  4598.7  165.29  4701.8  154.32  4721.6  150.06
  4809.0  146.83  4831.4  143.85  4840.6  139.93  4854.1  132.91  4904.1  128.91
  4970.4  125.32  5009.7  126.71  5096.4  124.16  5120.1  125.54  5136.2  129.72
  5155.4  136.31  5172.3  148.82  5254.4  151.81  5319.8  149.84  5321.0  153.93
  5338.4  154.06  5360.7  158.32  5448.3  182.61  5504.4  188.87  5595.2  213.25
#Mann=7,-1,0
  3975.9    0.06       0  3991.4    0.14       0  4115.4    0.08       0
  4285.1    0.12       0  4554.6    0.15       0  4840.6    0.04       0
  5172.3    0.15       0
#XS Ineff=2,0
    0.00 4582.80  168.00 5446.10    0.00  170.41
Permanent Ineff=
       F       F
Bank Sta=4840.6,5172.3
Exp/Cntr=0.5,0.3

Type RM Length L Ch R =3,6350,,,
BEGIN DESCRIPTION:
SALUDA RIVER (Riverbanks Zoo - TOR)
Structure ID: R_SAL_01
Detailed Survey Structure
END DESCRIPTION:
Bridge Culvert--1,0,-1,-1,0
Deck Dist Width WeirC Skew NumUp NumDn MinLoCord MaxHiCord MaxSubmerge Is_Ogee
90,20,3,,32,32,,,0.95,0,1,1,,
  3805.3  3869.8  3948.1  3993.4  4035.5  4082.9  4140.5  4234.9  4331.0  4408.5
  4536.4  4566.6  4595.3  4640.4  4640.4  4672.8  4672.8  5356.1  5356.1  5356.6
  5356.7  5406.0  5406.0  5419.5  5452.6  5485.5  5520.1  5544.2  5606.1  5662.2
  5720.9  5755.5
  182.97  180.97  174.55  173.50  171.43  168.82  169.06  169.40  167.74  168.63
  167.17  167.24  168.58  169.28  173.81  173.78  173.78  173.23  173.23  173.23
  173.77  173.18  168.82  168.86  170.79  173.49  177.22  178.71  185.09  191.46
  199.78  204.77
  104.16  104.16  104.16  104.16  104.16  104.16  104.16  104.16  104.16  104.16
  104.16  104.16  104.16  104.16  104.16  104.16  163.30  163.30  104.16  104.16
  104.16  104.16  104.16  104.16  104.16  104.16  104.16  104.16  104.16  104.16
  104.16  104.16
  3805.3  3869.8  3948.1  3993.4  4035.5  4082.9  4140.5  4234.9  4331.0  4408.5
  4536.4  4566.6  4595.3  4640.4  4640.4  4672.8  4672.8  5356.1  5356.1  5356.6
  5356.7  5406.0  5406.0  5419.5  5452.6  5485.5  5520.1  5544.2  5606.1  5662.2
  5720.9  5755.5
  182.97  180.97  174.55  173.50  171.43  168.82  169.06  169.40  167.74  168.63
  167.17  167.24  168.58  169.28  173.81  173.78  173.78  173.23  173.23  173.23
  173.77  173.18  168.82  168.86  170.79  173.49  177.22  178.71  185.09  191.46
  199.78  204.77
  104.16  104.16  104.16  104.16  104.16  104.16  104.16  104.16  104.16  104.16
  104.16  104.16  104.16  104.16  104.16  104.16  163.30  163.30  104.16  104.16
  104.16  104.16  104.16  104.16  104.16  104.16  104.16  104.16  104.16  104.16
  104.16  104.16
Pier Skew, UpSta & Num, DnSta & Num=,4721.6,2,4721.6,2,0,0,0,0,0
     2.5     2.5
  150.06  163.30
     2.5     2.5
  150.12  163.30
Pier Skew, UpSta & Num, DnSta & Num=,4831.4,2,4831.4,2,0,0,0,0,0
     2.5     2.5
  143.85  163.30
     2.5     2.5
  143.91  163.30
Pier Skew, UpSta & Num, DnSta & Num=,4995.9,2,4995.9,2,0,0,0,0,0
     2.5     2.5
  125.32  163.30
     2.5     2.5
  125.38  163.30
Pier Skew, UpSta & Num, DnSta & Num=,5161.1,2,5161.1,2,0,0,0,0,0
     2.5     2.5
  141.36  163.30
     2.5     2.5
  141.42  163.30
Pier Skew, UpSta & Num, DnSta & Num=,5271.2,2,5271.2,2,0,0,0,0,0
     2.5     2.5
  150.47  163.30
     2.5     2.5
  150.53  163.30
BR Coef=1,1,0,1.25,0,,,0.8,0,2,0,
WSPro=,,,, 1 ,,,, 0 ,,,, 0 ,,,,-1 ,-1 ,-1 , 0 , 0 , 0 , 0 , 0
BC Design=,,0,,0,,,,,,

Type RM Length L Ch R = 1,6270,350,370,353
BEGIN DESCRIPTION:
SALUDA RIVER (Riverbanks Zoo - DS)
END DESCRIPTION:
XS GIS Cut Line= 4
      1977521.00       792252.67      1977456.67       792007.05
      1976896.71       791316.44      1976509.18       790823.66
#Sta/Elev= 30
  3857.0  174.55  3874.6  170.48  3983.8  167.85  4147.4  169.55  4516.7  166.90
  4616.2  161.87  4680.2  152.18  4809.0  146.89  4825.1  142.92  4831.4  143.91
  4840.6  139.99  4844.6  136.38  4854.1  132.97  4904.1  128.97  4970.4  125.38
  5009.7  126.77  5096.4  124.22  5120.1  125.60  5136.2  129.78  5148.1  135.59
  5155.4  136.37  5172.3  148.88  5186.6  149.68  5289.5  151.37  5304.0  155.01
  5393.5  200.10  5424.6  205.60  5537.1  207.78  5596.3  212.80  5626.9  217.62
#Mann=8,-1,0
  3857.0    0.07       0  3874.6    0.14       0  3983.8    0.08       0
  4147.4    0.12       0  4516.7    0.15       0  4840.6    0.04       0
  5172.3    0.04       0  5186.6    0.15       0
#XS Ineff=2,0
    0.00 4602.80  168.70 5426.10    0.00  169.24
Permanent Ineff=
       F       F
Bank Sta=4840.6,5172.3
Exp/Cntr=0.5,0.3

Type RM Length L Ch R = 1,5900,475,500,577
BEGIN DESCRIPTION:
SALUDA RIVER 12.0
END DESCRIPTION:
XS GIS Cut Line= 3
      1977851.52       792172.26      1977193.90       791096.43
      1976744.60       790620.92
#Sta/Elev= 30
  3739.1  167.13  3753.6  164.17  3804.0  165.99  3980.4  169.81  4050.2  171.60
  4263.0  169.31  4380.2  163.03  4509.3  161.08  4600.1  163.49  4621.1  161.53
  4680.3  152.05  4757.2  147.94  4840.6  147.64  4854.1  140.62  4904.1  136.62
  4970.4  133.03  5096.4  131.87  5120.1  133.25  5155.4  144.02  5205.4  147.03
  5242.8  153.02  5311.3  155.60  5329.6  165.11  5362.2  169.15  5381.0  182.53
  5406.1  193.88  5428.1  208.09  5457.6  219.72  5613.8  253.38  5654.2  259.69
#Mann=6,-1,0
  3739.1    0.14       0  3804.0    0.08       0  3980.4    0.12       0
  4621.1    0.15       0  4840.6    0.04       0  5155.4    0.15       0
Bank Sta=4840.6,5155.4
Exp/Cntr=0.3,0.1

Type RM Length L Ch R = 1,5400,412,500,635
BEGIN DESCRIPTION:
SALUDA RIVER 11.0
END DESCRIPTION:
XS GIS Cut Line= 4
      1977950.89       792189.73      1977743.74       791163.13
      1977578.28       790778.61      1977338.60       790270.61
#Sta/Elev= 30
  3534.1  167.46  3564.2  163.80  3613.2  166.02  3777.4  169.69  4220.7  166.44
  4369.4  156.23  4401.3  159.02  4429.6  158.00  4448.8  152.87  4492.2  159.57
  4610.2  158.30  4629.6  158.57  4719.8  145.99  4785.9  146.73  4805.5  144.60
  4818.6  136.96  4860.2  139.76  4970.4  132.87  5096.4  131.71  5120.1  133.09
  5148.1  143.08  5210.9  152.98  5273.2  156.28  5290.9  162.45  5329.2  170.13
  5357.2  171.17  5391.3  170.63  5409.7  175.48  5472.2  182.24  5561.7  197.06
#Mann=7,-1,0
  3534.1    0.14       0  3613.2    0.08       0  3777.4    0.12       0
  4610.2    0.15       0  4805.5    0.04       0  5148.1    0.15       0
  5357.2    0.12       0
Bank Sta=4805.5,5148.1
Exp/Cntr=0.3,0.1

Type RM Length L Ch R = 1,4900,419,500,637
BEGIN DESCRIPTION:
SALUDA RIVER 10.0
END DESCRIPTION:
XS GIS Cut Line= 3
      1978001.90       792181.50      1978051.23       790671.10
      1978078.83       790209.63
#Sta/Elev= 30
  3488.8  166.33  3509.4  163.63  3560.9  165.69  3728.3  170.31  3918.4  171.07
  4014.3  166.90  4031.0  160.55  4052.4  160.33  4072.2  168.72  4080.1  168.77
  4118.5  165.40  4223.6  164.94  4324.2  158.90  4345.6  154.04  4367.5  157.51
  4542.2  155.18  4597.8  154.21  4621.5  149.07  4692.3  143.43  4840.6  146.67
  4854.1  139.65  4904.1  135.65  5096.4  130.90  5120.1  132.28  5148.1  142.27
  5182.4  152.96  5292.1  224.43  5322.6  238.80  5389.2  251.98  5462.3  254.89
#Mann=7,-1,0
  3488.8    0.14       0  3560.9    0.08       0  3728.3    0.12       0
  4542.2    0.15       0  4840.6    0.04       0  5148.1    0.15       0
  5389.2    0.12       0
Bank Sta=4840.6,5148.1
Exp/Cntr=0.3,0.1

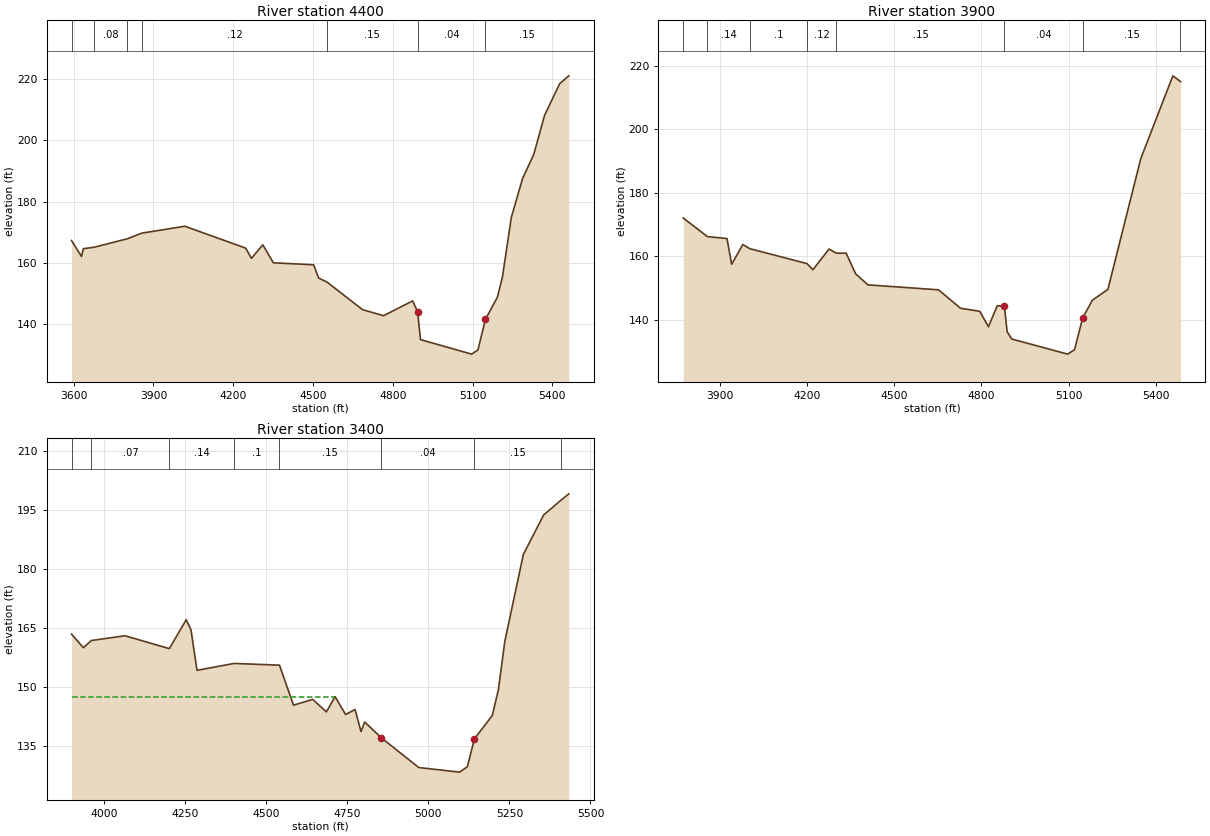
Type RM Length L Ch R = 1,4400,514,500,484
BEGIN DESCRIPTION:
SALUDA RIVER 9.0
END DESCRIPTION:
XS GIS Cut Line= 4
      1978081.87       792189.71      1978292.06       791230.15
      1978500.08       790858.87      1978785.55       790496.00
#Sta/Elev= 30
  3592.1  167.26  3629.8  162.04  3636.5  164.59  3678.2  165.09  3801.3  167.82
  3856.1  169.68  4018.0  171.94  4246.9  164.78  4268.6  161.42  4311.1  165.86
  4351.2  159.97  4502.4  159.33  4521.2  154.97  4552.7  153.67  4686.2  144.64
  4765.4  142.67  4874.5  147.51  4893.2  143.98  4904.1  134.84  5096.4  130.09
  5120.1  131.47  5148.1  141.46  5193.0  148.69  5212.0  155.23  5245.6  174.84
  5287.7  187.52  5329.6  195.37  5370.5  208.22  5427.4  218.59  5461.7  221.16
#Mann=7,-1,0
  3592.1    0.14       0  3678.2    0.08       0  3801.3     0.1       0
  3856.1    0.12       0  4552.7    0.15       0  4893.2    0.04       0
  5148.1    0.15       0
Bank Sta=4893.2,5148.1
Exp/Cntr=0.3,0.1

Type RM Length L Ch R = 1,3900,545,500,485
BEGIN DESCRIPTION:
SALUDA RIVER 8.0
END DESCRIPTION:
XS GIS Cut Line= 3
      1978348.12       792311.51      1978863.56       791199.24
      1979100.50       790776.28
#Sta/Elev= 30
  3774.1  172.08  3857.2  166.23  3924.5  165.62  3940.6  157.53  3979.0  163.74
  4003.0  162.43  4199.7  157.74  4220.1  155.80  4275.6  162.33  4300.8  161.01
  4334.5  161.02  4367.0  154.53  4409.2  151.06  4652.2  149.49  4727.9  143.70
  4794.1  142.74  4823.9  137.88  4854.1  144.48  4878.8  144.36  4888.2  136.34
  4904.1  134.02  5096.4  129.27  5120.1  130.65  5148.1  140.64  5181.6  146.23
  5234.9  149.64  5348.0  190.75  5458.4  216.79  5483.6  215.08  5484.8  214.97
#Mann=8,-1,0
  3774.1    0.07       0  3857.2    0.14       0  4003.0     0.1       0
  4199.7    0.12       0  4300.8    0.15       0  4878.8    0.04       0
  5148.1    0.15       0  5483.6    0.11       0
Bank Sta=4878.8,5148.1
Exp/Cntr=0.3,0.1

Type RM Length L Ch R = 1,3400,568,500,286
BEGIN DESCRIPTION:
SALUDA RIVER 7.0
END DESCRIPTION:
XS GIS Cut Line= 3
      1979024.36       792530.86      1979286.73       791461.47
      1979423.42       791050.40
#Sta/Elev= 30
  3898.9  163.48  3935.5  160.04  3960.1  161.86  4063.8  163.07  4200.6  159.80
  4252.8  167.14  4267.6  164.53  4286.1  154.30  4400.1  156.04  4540.5  155.61
  4583.8  145.45  4643.1  146.92  4685.2  143.75  4712.0  147.62  4744.5  143.08
  4773.8  144.35  4792.0  138.75  4803.5  141.18  4854.1  137.21  4970.4  129.62
  5096.4  128.46  5120.1  129.84  5142.2  136.93  5197.1  142.83  5216.0  149.41
  5235.7  161.63  5293.0  183.71  5355.5  193.72  5409.6  197.51  5433.2  199.09
#Mann=8,-1,0
  3898.9    0.06       0  3960.1    0.07       0  4200.6    0.14       0
  4400.1     0.1       0  4540.5    0.15       0  4854.1    0.04       0
  5142.2    0.15       0  5409.6    0.11       0
#XS Ineff=2,0
    0.00 4710.00  147.65               0
Permanent Ineff=
       F       F
Bank Sta=4854.1,5142.2
Exp/Cntr=0.3,0.1