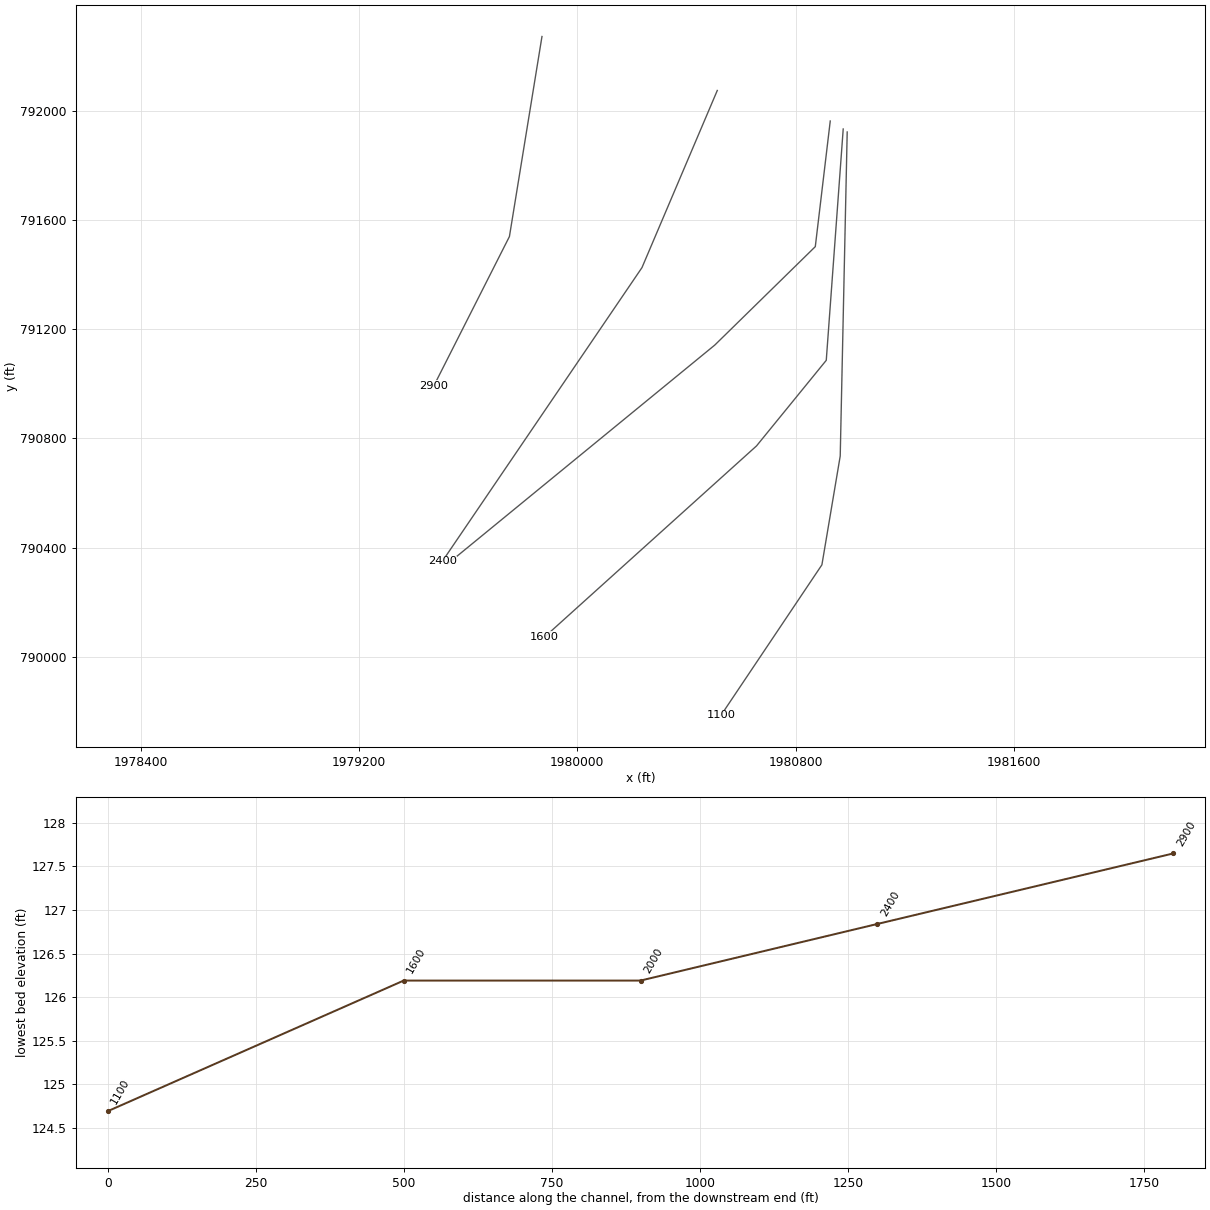
HEC-RAS study SALUDA RIVER.prj: SALUDA RIVER Detailed Study

--- SALUDA RIVER.g01 (geometry) --- (continued)

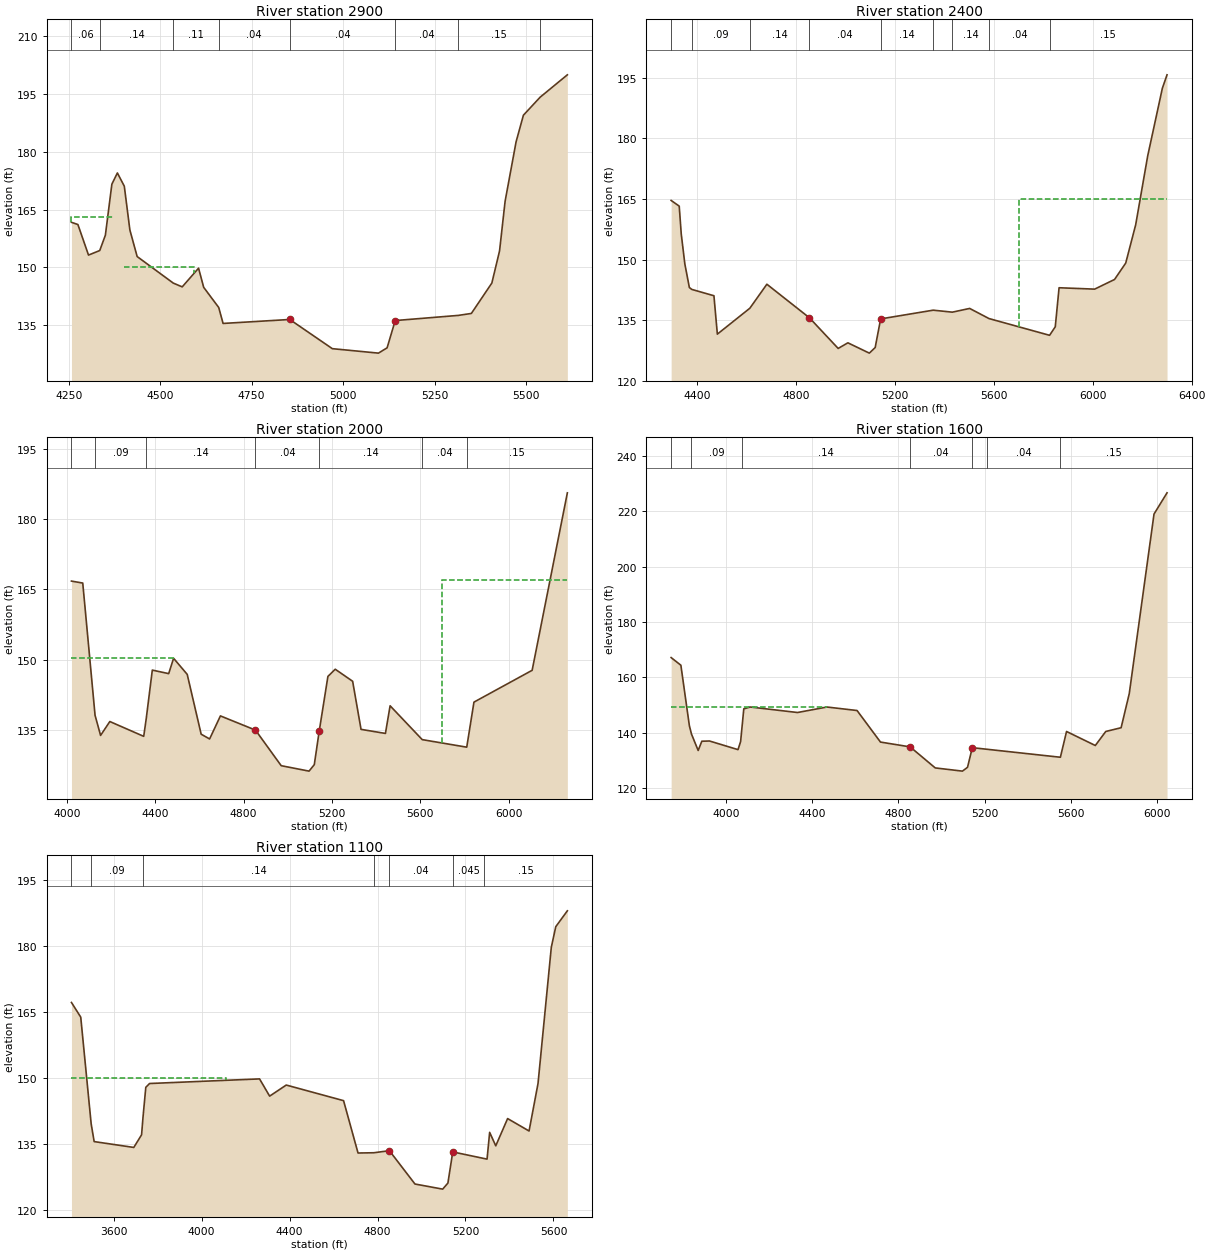
Type RM Length L Ch R = 1,2900,561,500,633
BEGIN DESCRIPTION:
SALUDA RIVER 6.0
END DESCRIPTION:
XS GIS Cut Line= 3
      1979870.59       792271.95      1979751.35       791539.18
      1979474.64       790992.64
#Sta/Elev= 30
  4257.6  161.67  4275.2  161.10  4304.2  153.15  4334.9  154.33  4350.3  158.33
  4368.0  171.59  4383.1  174.51  4402.0  171.06  4417.2  159.69  4437.1  152.77
  4535.7  145.87  4560.2  144.88  4604.9  149.74  4618.9  144.76  4660.0  139.52
  4671.9  135.37  4854.1  136.40  4970.4  128.81  5096.4  127.65  5120.1  129.03
  5142.2  136.12  5314.5  137.46  5350.3  137.97  5406.3  145.88  5427.3  154.22
  5442.5  167.15  5472.5  182.61  5492.5  189.53  5538.3  194.22  5612.6  200.03
#Mann=8,-1,0
  4257.6    0.06       0  4334.9    0.14       0  4535.7    0.11       0
  4660.0    0.04       0  4854.1    0.04       0  5142.2    0.04       0
  5314.5    0.15       0  5538.3    0.11       0
#XS Ineff=2,-1
 4250.00 4370.00  163.00 4400.00 4592.30  150.15
Permanent Ineff=
       F       F
Bank Sta=4854.1,5142.2
Exp/Cntr=0.3,0.1

Type RM Length L Ch R = 1,2400,496,400,119
BEGIN DESCRIPTION:
SALUDA RIVER 5.0
END DESCRIPTION:
XS GIS Cut Line= 3
      1980512.75       792074.32      1980236.87       791425.43
      1979505.82       790349.97
#Sta/Elev= 30
  4294.9  164.63  4327.6  163.22  4335.8  156.33  4350.3  148.93  4368.6  143.08
  4378.5  142.61  4468.0  141.04  4481.8  131.54  4613.2  137.95  4682.1  143.89
  4854.1  135.59  4970.4  128.00  5009.7  129.39  5096.4  126.84  5120.1  128.22
  5142.2  135.31  5354.8  137.47  5432.1  136.98  5502.2  137.90  5580.6  135.39
  5825.4  131.25  5848.4  133.36  5863.8  143.02  6007.7  142.68  6088.1  145.07
  6133.3  149.12  6173.6  158.60  6222.2  175.65  6281.5  192.40  6300.4  195.72
#Mann=9,-1,0
  4294.9    0.06       0  4378.5    0.09       0  4613.2    0.14       0
  4854.1    0.04       0  5142.2    0.14       0  5354.8    0.04       0
  5432.1    0.14       0  5580.6    0.04       0  5825.4    0.15       0
#XS Ineff=2,0
       0                 5700.00    0.00  165.00
Permanent Ineff=
       F       F
Bank Sta=4854.1,5142.2
Exp/Cntr=0.3,0.1

Type RM Length L Ch R = 1,2000,391,400,436
BEGIN DESCRIPTION:
SALUDA RIVER 4.0
END DESCRIPTION:
XS GIS Cut Line= 4
      1980926.55       791962.41      1980871.77       791502.24
      1980503.74       791141.86      1979525.11       790340.31
#Sta/Elev= 30
  4021.5  166.73  4072.6  166.31  4128.3  138.09  4153.3  133.81  4195.1  136.77
  4348.4  133.61  4359.7  137.36  4387.3  147.74  4461.4  146.99  4483.6  150.26
  4545.2  146.83  4608.3  134.07  4646.5  133.05  4695.4  137.97  4854.1  134.94
  4970.4  127.35  5096.4  126.19  5120.1  127.57  5142.2  134.66  5181.7  146.39
  5214.8  147.93  5293.6  145.36  5331.6  135.10  5441.9  134.23  5463.1  140.13
  5608.4  132.91  5809.8  131.30  5842.4  140.91  6105.7  147.70  6265.0  185.56
#Mann=7,-1,0
  4021.5    0.06       0  4128.3    0.09       0  4359.7    0.14       0
  4854.1    0.04       0  5142.2    0.14       0  5608.4    0.04       0
  5809.8    0.15       0
#XS Ineff=2,0
    0.00 4483.60  150.30 5700.00    0.00  167.00
Permanent Ineff=
       F       F
Bank Sta=4854.1,5142.2
Exp/Cntr=0.3,0.1

Type RM Length L Ch R = 1,1600,406,500,615
BEGIN DESCRIPTION:
SALUDA RIVER 3.0
END DESCRIPTION:
XS GIS Cut Line= 4
      1980974.03       791933.21      1980911.94       791085.89
      1980656.51       790772.36      1979880.37       790072.62
#Sta/Elev= 30
  3746.0  167.18  3791.2  164.42  3830.6  142.56  3840.4  139.56  3871.4  133.64
  3888.2  136.98  3923.8  137.07  4056.0  133.95  4068.1  136.85  4073.3  141.01
  4082.9  148.68  4113.3  149.33  4332.1  147.35  4468.4  149.33  4608.0  148.07
  4716.5  136.68  4854.1  134.94  4970.4  127.35  5096.4  126.19  5120.1  127.57
  5142.2  134.66  5212.6  134.06  5550.6  131.20  5579.1  140.50  5712.5  135.44
  5760.9  140.50  5832.1  141.86  5869.9  154.17  5984.7  219.01  6045.0  226.66
#Mann=7,-1,0
  3746.0    0.06       0  3840.4    0.09       0  4073.3    0.14       0
  4854.1    0.04       0  5142.2    0.14       0  5212.6    0.04       0
  5550.6    0.15       0
#XS Ineff=2,0
    0.00 4468.40  149.35               0
Permanent Ineff=
       F       F
Bank Sta=4854.1,5142.2
Exp/Cntr=0.3,0.1

Type RM Length L Ch R = 1,1100,576,500,474
BEGIN DESCRIPTION:
SALUDA RIVER 2.0
END DESCRIPTION:
XS GIS Cut Line= 4
      1980988.64       791922.27      1980963.07       790735.28
      1980895.99       790336.75      1980526.61       789785.94
#Sta/Elev= 30
  3408.6  167.18  3450.8  163.84  3498.1  139.60  3511.8  135.51  3692.0  134.18
  3727.4  137.06  3733.9  141.06  3746.6  147.86  3763.7  148.73  4263.8  149.78
  4309.6  145.86  4385.2  148.38  4645.7  144.83  4711.5  132.91  4783.3  132.97
  4854.1  133.44  4970.4  125.85  5096.4  124.69  5120.1  126.07  5142.2  133.16
  5285.6  131.65  5298.1  131.52  5309.9  137.61  5337.7  134.55  5391.6  140.75
  5489.1  137.92  5529.8  148.73  5590.2  179.73  5610.5  184.43  5663.2  188.04
#Mann=7,-1,0
  3408.6    0.06       0  3498.1    0.09       0  3733.9    0.14       0
  4783.3   0.045       0  4854.1    0.04       0  5142.2   0.045       0
  5285.6    0.15       0
#XS Ineff=2,0
    0.00 4112.50  149.90               0
Permanent Ineff=
       F       F
Bank Sta=4854.1,5142.2
Exp/Cntr=0.3,0.1

Chan Stop Cuts=-1